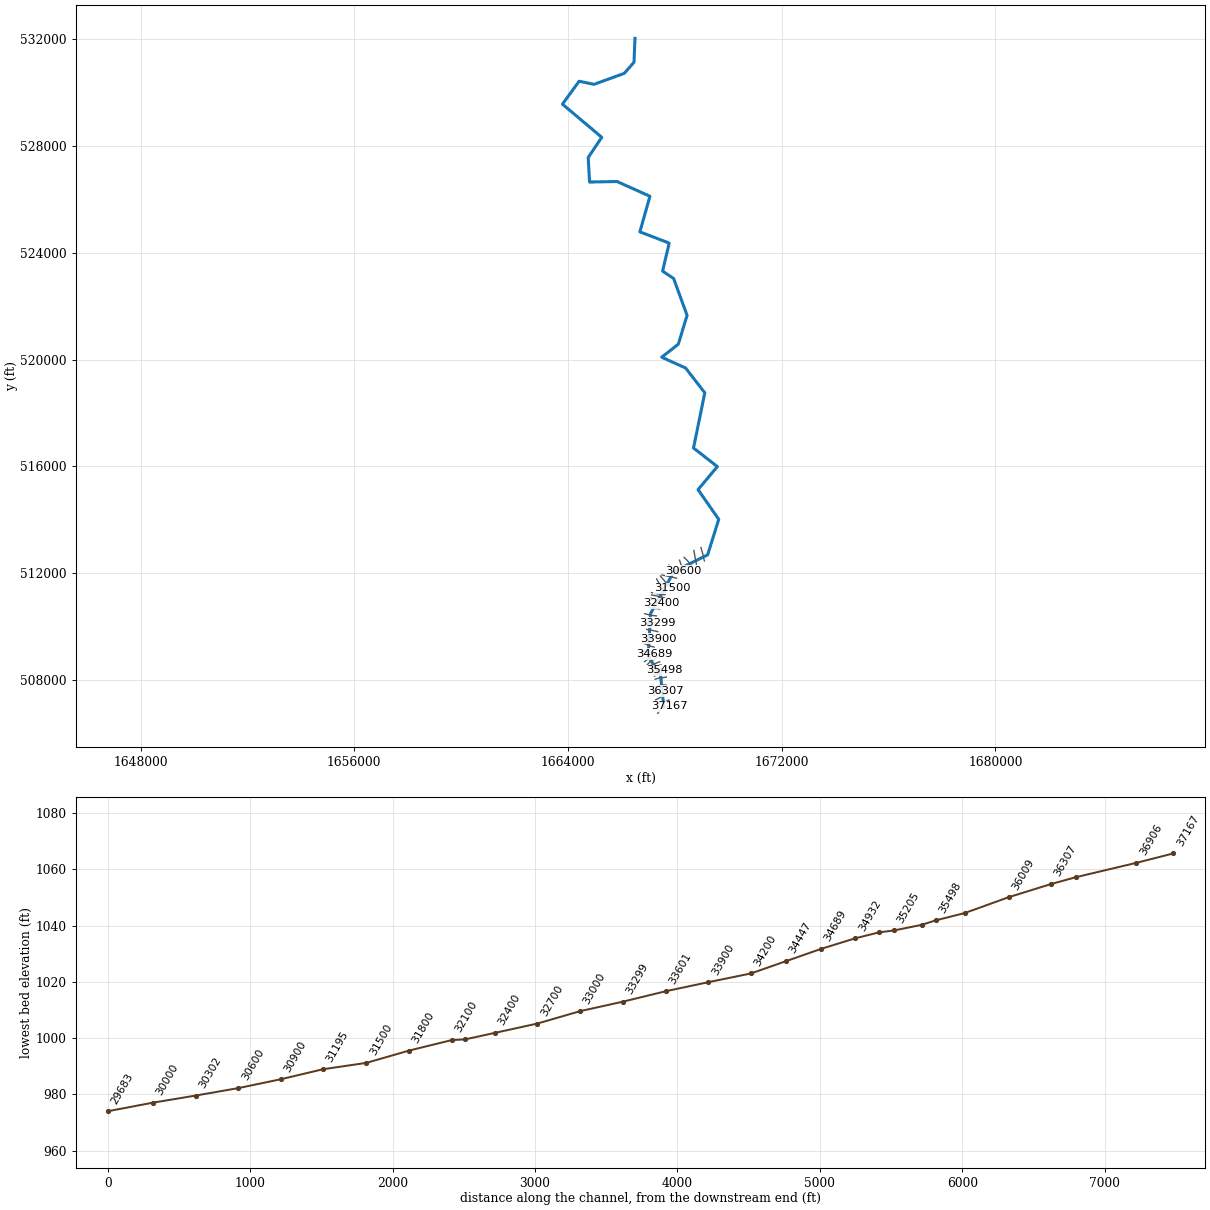
--- WlfRn.prj (project) ---

Proj Title=WlfRn
Current Plan=p01
Default Exp/Contr=0,0
English Units
Geom File=g01
Flow File=f01
Plan File=p01
BEGIN DESCRIPTION:
---------- MODELED AS PART OF WVEM CTP PROGRAM, 2025----------
Stream Name: Wolf Run
Flood Zone: AFH
Marshall County, WV
HEC-RAS Version: RAS 6.6
Vertical Datum: NAVD88
Projection: NAD 1983 StatePlane West Virginia N FIPS 4701 (US Feet)
Terrain: 1-meter West Virginia FEMA R3 South Central (collected 2018-2019)
Land Use: 2024 NLCD
Hydrologic Method:
Duda et al., "Estimation of magnitude and frequency of floods for rural, unregulated streams in and near Virginia and West Virginia." September 8, 2025.
Additional Model Notes:
Large dam ~RS 1400
END DESCRIPTION:
DSS Export Rating Curves= 0
DSS Export Rating Curve Sorted= 0
DSS Export Volume Flow Curves= 0
DXF OffsetX= 0
DXF OffsetY= 0
DXF ScaleX= 0
DXF ScaleY= 0

--- WlfRn.p01 (plan) ---

Plan Title=Floodplain
Program Version=6.60
Short Identifier=Floodplain
Geom File=g01
Flow File=f01
Subcritical Flow
K Sum by GR= 0
Std Step Tol= 0.01
Critical Tol= 0.01
Num of Std Step Trials= 20
Max Error Tol= 0.3
Flow Tol Ratio= 0.001
Split Flow NTrial= 30
Split Flow Tol= 0.02
Split Flow Ratio= 0.02
Log Output Level= 0
Friction Slope Method= 1
Unsteady Friction Slope Method= 2
Unsteady Bridges Friction Slope Method= 1
Parabolic Critical Depth
Global Vel Dist= 0 , 0 , 0
Global Log Level= 0
CheckData=False
Encroach Param=-1 ,0,0, 0
Flow Ratio Tolerance=0.1
Flow Ratio Min Ratio=0.5
Flow Ratio Max Ratio=4
Flow Ratio Max Iterations= 10
Mapping Interval=1HOUR
Computation Time Step Use Courant=        0
Computation Time Step Use Time Series=    0
Computation Time Step Count To Double=0
Computation Time Step Max Doubling=0
Computation Time Step Max Halving=0
Computation Time Step Residence Courant=0
Run HTab= 0
Run UNet= 0
Run Sediment= 0
Run PostProcess= 0
Run WQNet= 0
Run RASMapper=-1
UNET Theta= 0
UNET Theta Warmup= 0
UNET ZTol= 0
UNET ZSATol= 0
UNET MxIter= 0
UNET Max Iter WO Improvement= 0
UNET MaxInSteps= 0
UNET DtIC= 0
UNET DtMin= 0
UNET MaxCRTS= 0
UNET WFStab= 0
UNET SFStab= 0
UNET WFX= 1
UNET SFX= 1
UNET Gravity=32.17405
UNET 1D Methodology=Finite Difference
UNET DSS MLevel= 1
UNET Pardiso=0
UNET DZMax Abort= 0
UNET Use Existing IB Tables= 0
UNET Froude Reduction=False
UNET Froude Limit= 0
UNET Froude Power= 0
UNET D1 Cores= 0
UNET WindReference=Eulerian
UNET WindDragFormulation=Hsu (1988)
UNET D2 Coriolis=0
UNET D2 Cores= 0
UNET D2 Theta= 1
UNET D2 Theta Warmup= 1
UNET D2 Z Tol= 0.01
UNET D2 Volume Tol= 0.01
UNET D2 Max Iterations= 20
UNET D2 Advanced Convergence=0
UNET D2 WS Max Tol=0.15
UNET D2 WS RMS Tol=0.002
UNET D2 WS Stall Tol=1
UNET D2 Equation= 0
UNET D2 RampUpFraction=0.1
UNET D2 TimeSlices= 1
UNET D2 Turbulence Formulation=Non-Conservative (original)
UNET D2 Eddy Viscosity=0.3
UNET D2 Transverse Eddy Viscosity=0.1
UNET D2 Smagorinsky Mixing=0
UNET D2 BCVolumeCheck=0
UNET D2 Cores=0
UNET D2 SolverType=PARDISO (Direct)
UNET D2 Minimum Iterations= 3
UNET D2 Maximum Iterations= 30
UNET D2 Restart Number= 10
UNET D2 Relaxation Coeff=1.3
UNET D2 SOR Precondition Iterations= 10
UNET D2 ILUT Maximum Fill= 8
UNET D2 ILUT Tolerance=1E-08
UNET D2 Convergence Tolerance=0.00001
PS Theta= 1
PS WS Tol= 0.01
PS Volume Tol= 0.01
PS Max Iterations= 20
PS Equation= 0
PS Advance Time Step=-1
PS Target Courant=0.9
PS Time Slices= 1
PS Iterate With 2D=0
PS Project Initial WSE from DS=-1
PS Ramp Up Initial WSE from US=-1
PS Cores=0
UNET D1D2 MaxIter= 0
UNET D1D2 ZTol=0.01
UNET D1D2 QTol=0.1
UNET D1D2 MinQTol=1
Write IC File= 0
Write IC File at Fixed DateTime=0
Write IC File at Sim End=0
Echo Input=False
Echo Parameters=False
Echo Output=False
Write Detailed= 0
HDF Write Warmup=0
HDF Write Time Slices=0
HDF Flush=0
HDF Compression= 1
HDF Chunk Size= 1
HDF Spatial Parts= 1
HDF Use Max Rows=0
HDF Fixed Rows= 1
Calibration Method= 0
Calibration Iterations= 20
Calibration Max Change=0.05
Calibration Tolerance=0.2
Calibration Maximum=1.5
Calibration Minimum=0.5
Calibration Optimization Method= 1
WQ AD Non Conservative
WQ ULTIMATE=-1
WQ Max Comp Step=1HOUR
WQ Output Interval=15MIN
WQ Output Selected Increments= 0
WQ Create Restart=0
WQ Fixed Restart=0
WQ System Summary=0
WQ Write To DSS=0
Sorting and Armoring Iterations= 10
XS Update Threshold= 0.02
Bed Roughness Predictor= 0
Processes Affected by Predictor=Sediment Only
Hydraulics Update Threshold= 0.02
Energy Slope Method= 1
Volume Change Method= 1
Sediment Retention Method= 0
Sediment TS Multiplier= 1
Warm Up Method= 0
XS Weighting Method= 0
Number of US Weighted Cross Sections= 1
Number of DS Weighted Cross Sections= 1
Upstream XS Weight=0
Main XS Weight=1
Downstream XS Weight=0
Number of DS XS's Weighted with US Boundary= 1
Upstream Boundary Weight= 1
Weight of XSs Associated with US Boundary= 0
Number of US XS's Weighted with DS Boundary= 1
Downstream Boundary Weight= 0.5
Weight of XSs Associated with DS Boundary= 0.5
Percentile Method= 0
Sediment Output Level= 3
Mass or Volume Output= 0
Output Increment Type= 1
Profile and TS Output Increment= 1
Transport Output Increment 1
XS Output Flag= 0
XS Output Increment= 10
Read HDF5 Sediment Hotstart= 0
Sediment Hotstart Type= 0
Write Gradation File= 0
Read Gradation Hotstart= 0
Write HDF5 File= 1
Write Binary Output= 1
Write DSS Sediment File= 0
DSS Sediment Output Type= 1
SV Curve= 0
Specific Gage Flag= 0
Subcell Erosion Methods= 0
Subcell Deposition Methods= 0
Advection Scheme= 1
Matrix Solver= 0
Implicit Weighting Factor= 1
Maximum Outer Loop Convergence Iterations= 5
Convergence Maximum Absolute= 0.001
Convergence RMSE= 0.0001
Grain Fractions Max Abs Error= 0.001
Max Subgrid Regions= 1
Max Subgrid Length Scale= 3.402823E+38
Initial Layer Thickness= 3
Min Layer Thickness= 0.1
Max Layer Thickness= 6
Number of Layers= 5

--- WlfRn.f01 (steady flow) ---

Flow Title=Flow
Program Version=6.60
Number of Profiles= 1
Profile Names=P100yr
River Rch & RM=WlfRn,Main,37167
    1090
River Rch & RM=WlfRn,Main,32700
    1350
River Rch & RM=WlfRn,Main,29683
    2390
River Rch & RM=WlfRn,Main,25792
    2660
River Rch & RM=WlfRn,Main,16158
    3440
Boundary for River Rch & Prof#=WlfRn,Main            , 1
Up Type= 0
Dn Type= 3
Dn Slope=0.018646
DSS Import GetInterval= 0
DSS Import GetPeak= 0
DSS Import FillOption= 0

--- WlfRn.g01 (geometry) ---

Geom Title=Geometry
Program Version=6.60

River Reach=WlfRn           ,Main
Reach XY= 30
     1667587.868      506966.484     1667464.696      508194.739
     1666999.881      508882.393      1667089.63      510489.588
     1667966.975      512068.954     1669225.885      512689.319
      1669642.46      514020.472     1668867.082      515133.722
     1669590.902      515995.301     1668698.111      516692.408
     1669120.336      518759.459     1668402.878      519688.077
     1667508.553      520092.526     1668129.446      520581.656
     1668457.092      521663.336     1667951.886      523044.383
      1667539.68      523318.645     1667787.738        524367.3
     1666690.316      524789.252     1667067.365      526121.472
     1665836.917      526673.752     1664806.722      526654.634
     1664755.887      527574.545     1665263.456      528330.764
     1663792.431      529571.875     1664416.446      530430.399
     1664976.618      530314.964     1666108.075      530727.527
      1666470.58      531142.207     1666506.963      532037.659

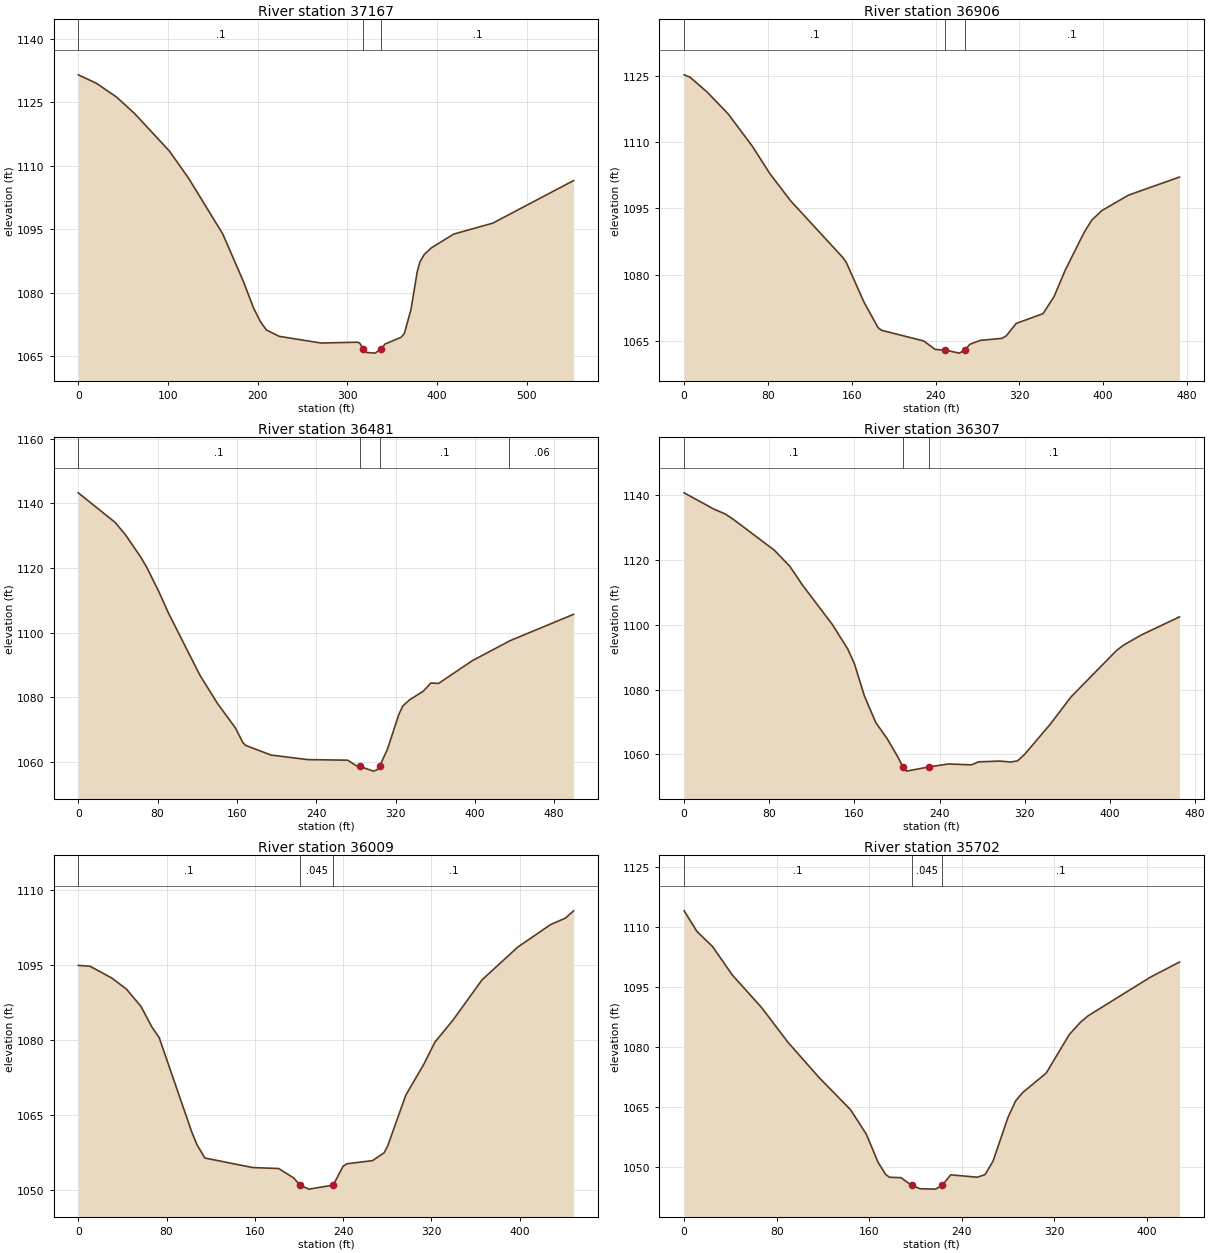
Type RM Length L Ch R = 1 ,37167   ,256.7,260.8,256.1
XS GIS Cut Line= 4
1667363.90057256506751.6030110461667469.69695262506928.873244478
1667640.50290421507003.5954920131667799.30261219507019.761073463
#Sta/Elev= 30
       0 1131.46    20.4 1129.44    42.7  1126.2    63.1 1122.25   101.4  1113.5
   122.9 1107.07   161.2 1093.84   184.1 1082.65   195.6 1076.31   203.2 1073.12
   209.8 1071.17   224.1 1069.66   270.7 1068.08   311.3 1068.27   313.7 1068.11
  317.711066.774   321.3 1065.85   331.2 1065.69  338.051066.773   342.3 1067.85
   360.2 1069.44   363.8 1070.37   371.1    1076   378.1 1084.92   381.1 1087.27
     386 1089.01   393.6 1090.53   418.8 1093.82   462.5 1096.42   552.5 1106.47
#Mann= 3 ,-1,0
       0      .1       0  317.71    .045       0  338.05      .1       0
Bank Sta=317.71,338.05
XS Rating Curve= 0 ,0
Exp/Cntr=0.3,0.1

Type RM Length L Ch R = 1 ,36906   ,415.6,425,428
XS GIS Cut Line= 5
 1667326.3463175507128.510318846 1667426.8110116507143.837715998
1667520.59658517 507161.133285091667633.70593901507189.303504333
1667778.48447827 507255.60375753
#Sta/Elev= 30
       0 1125.17     5.6 1124.64      22 1121.27    41.9 1116.38    65.2 1109.01
    81.7  1102.9   101.6 1096.73   151.7 1083.86     155 1082.69   171.7 1073.83
   185.1 1068.09   188.4 1067.49   228.8 1065.07   239.7 1063.15   249.1 1063.02
   262.7 1062.33   267.91063.018   272.8 1064.34   282.8 1065.21   303.2 1065.66
   307.4 1066.22     317 1069.04   342.6 1071.24   353.1  1075.1   363.9 1081.13
   381.9 1089.63   389.1 1092.35   398.5 1094.48   424.2 1098.01   472.8 1102.08
#Mann= 3 ,-1,0
       0      .1       0   249.1    .045       0   267.9      .1       0
Bank Sta=249.1,267.9
XS Rating Curve= 0 ,0
Exp/Cntr(USF)=0,0
Exp/Cntr=0.3,0.1

Type RM Length L Ch R = 1 ,36481   ,175.5,174.3,169.6
XS GIS Cut Line= 4
1667282.56213097507259.7962587531667431.35425317507336.282891819
1667549.14648298507424.6270641791667707.17331061507520.848274479
#Sta/Elev= 30
       0 1143.25    37.2 1134.09    47.9 1130.14    62.6 1123.57    68.9  1120.3
    81.1  1112.8    90.8 1106.18   122.5 1086.97   140.1 1078.28   158.5 1070.56
   165.9  1066.1   168.7 1065.19   194.4 1062.19   231.4 1060.78   271.8  1060.6
   280.6 1058.85     2841058.699   297.6 1057.22   301.1 1057.58   303.9  1058.7
   311.7 1063.88   323.5 1074.88   327.4 1077.39   333.8 1079.17     348 1081.94
   355.7 1084.48   363.4 1084.33   397.5 1091.37   435.7 1097.57   499.6 1105.69
#Mann= 4 ,-1,0
       0      .1       0     284    .045       0   303.9      .1       0
  434.54     .06       0
Bank Sta=284,303.9
XS Rating Curve= 0 ,0
Exp/Cntr(USF)=0,0
Exp/Cntr=0.3,0.1

Type RM Length L Ch R = 1 ,36307   ,293,297.5,292.2
XS GIS Cut Line= 6
1667226.88654268507428.8804530051667301.15575109507475.064415753
1667364.81999384507514.6539034991667463.16067642507558.515692428
1667552.45741384507572.5438795831667655.67571133507590.756441593
#Sta/Elev= 30
       0 1140.79    27.9 1135.76    38.4 1134.28    46.2  1132.6    84.8 1123.04
    99.3 1118.07   111.2 1112.26   138.9 1100.25   153.8 1092.47     160 1087.93
   169.3 1078.06     180 1069.81   190.8 1064.77     201 1059.03  205.461056.063
   208.8 1054.79   229.61056.063   248.3    1057   269.9 1056.73   276.5 1057.65
   296.5  1057.9   306.4 1057.61   313.1 1057.94   319.7 1059.91   343.8 1069.24
   363.5 1077.75   406.2 1092.06   412.8 1093.72   429.5 1096.87   465.3 1102.45
#Mann= 3 ,-1,0
       0      .1       0  205.46    .045       0   229.6      .1       0
Bank Sta=205.46,229.6
XS Rating Curve= 0 ,0
Exp/Cntr(USF)=0,0
Exp/Cntr=0.3,0.1

Type RM Length L Ch R = 1 ,36009   ,305.4,307.3,300.3
XS GIS Cut Line= 6
1667239.12306675507749.021873087   1667328.12781507758.691473171
1667397.33830151507787.7088035941667495.08974643 507817.46694617
  1667580.599746507816.2428672611667677.13137709507810.027000427
#Sta/Elev= 30
       0 1094.98    10.6 1094.81    30.4 1092.44    43.6 1090.23    56.8 1086.76
    66.7 1082.63    73.3 1080.51   102.8  1061.6   107.6 1059.02   114.7 1056.35
     158 1054.44   181.7 1054.24   195.4 1052.33  200.841050.915   209.1 1050.11
  231.091050.915     240 1054.69   243.4 1055.19   266.8 1055.83   277.3 1057.41
   280.5 1058.78   296.9 1068.96   313.3 1075.18   323.2 1079.56   339.6 1083.98
     366 1092.08   398.7  1098.7   428.3 1103.18   441.5 1104.44     449 1105.92
#Mann= 3 ,-1,0
       0      .1       0  200.84    .045       0  231.09      .1       0
Bank Sta=200.84,231.09
XS Rating Curve= 0 ,0
Exp/Cntr(USF)=0,0
Exp/Cntr=0.3,0.1

Type RM Length L Ch R = 1 ,35702   ,196.8,204.5,205.2
XS GIS Cut Line= 6
1667258.85793543508031.4025419211667343.83414343508056.305051178
1667417.43799885 508075.953305841667516.91253743508087.015619665
1667591.48423867508095.8079249261667678.01162468 508112.19667168
#Sta/Elev= 30
       0 1114.07      11 1108.93    24.6 1105.12    41.7 1097.99    66.9 1089.89
    89.6 1081.24   116.7 1072.35   143.9 1064.31   157.5 1058.17   167.6 1051.18
   174.2 1048.14   177.5 1047.45   187.4 1047.35  196.721045.409   203.9 1044.59
   217.1 1044.49  222.95 1045.41   230.3 1048.06   253.4 1047.47     260 1048.12
   266.9 1051.48   279.8  1062.4   286.4 1066.53   292.5 1068.63   312.9 1073.51
   332.7 1083.09   342.6 1086.25   349.3 1087.86   402.7 1097.45     428 1101.26
#Mann= 3 ,-1,0
       0      .1       0  196.72    .045       0  222.95      .1       0
Bank Sta=196.72,222.95
XS Rating Curve= 0 ,0
Exp/Cntr(USF)=0,0
Exp/Cntr=0.3,0.1

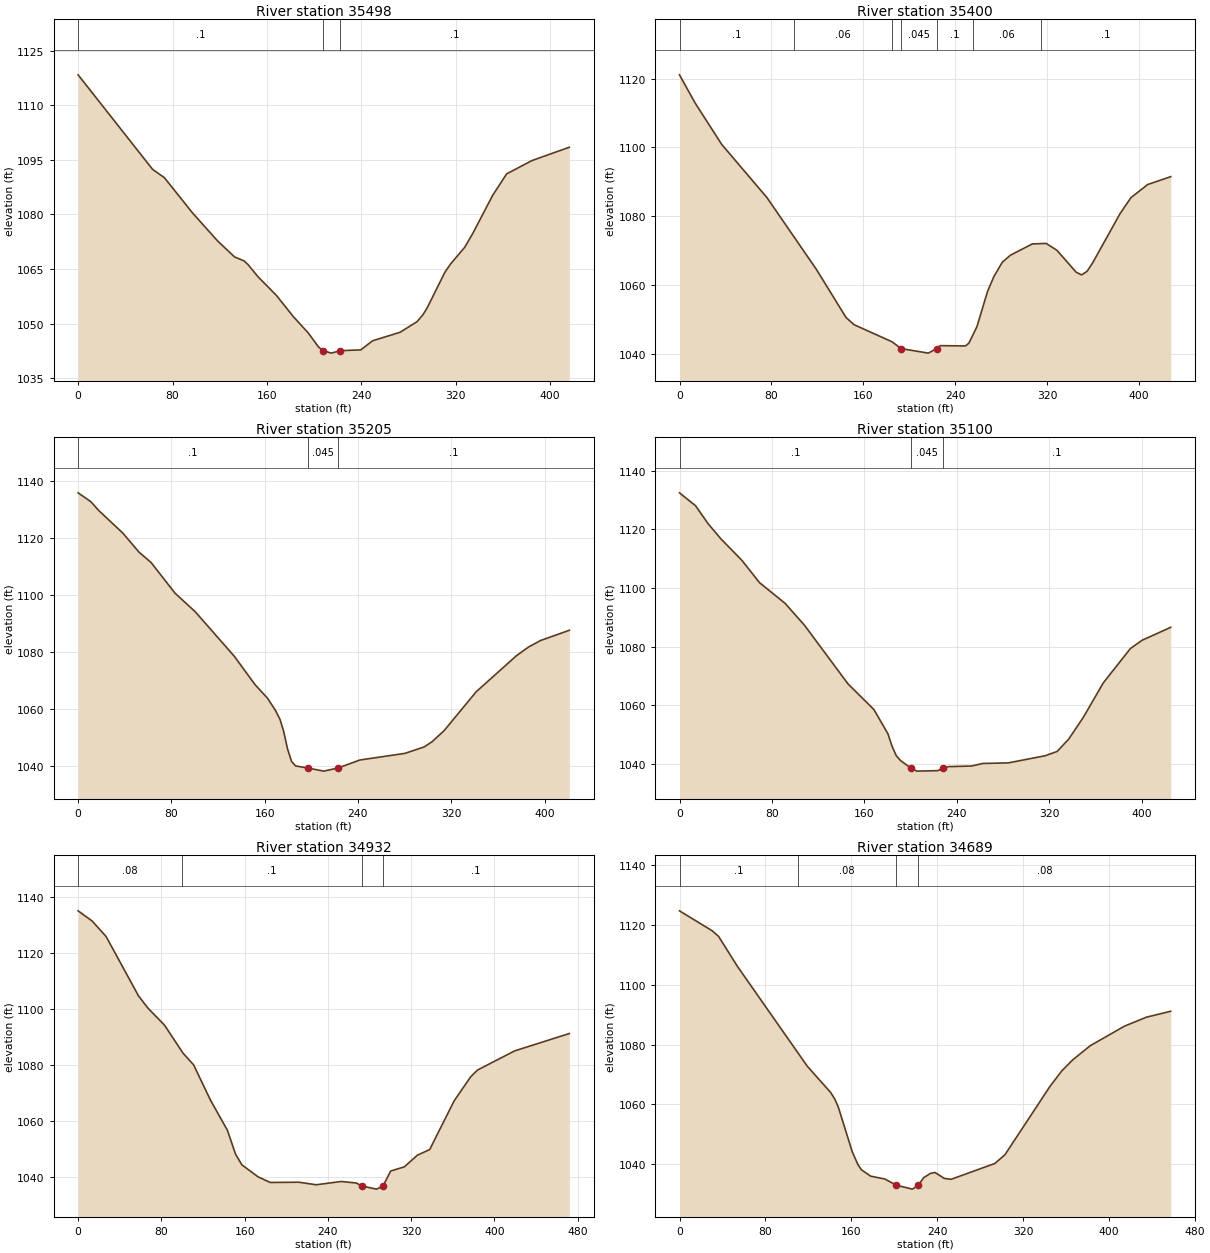
Type RM Length L Ch R = 1 ,35498   ,91.5,97.7,99.3
XS GIS Cut Line= 2
1667235.76414574508144.9612129991667587.37395173508367.588527346
#Sta/Elev= 30
       0  1118.4    63.1 1092.41    73.1 1090.13    96.8 1080.49   118.2 1072.72
   132.5 1068.35   140.7 1067.22     144 1066.22   152.4 1062.89   167.9  1057.8
   182.4 1051.91   195.1 1047.39   203.8 1043.53  207.651042.552   214.5 1041.88
   222.3 1042.56   239.5 1042.77   249.5 1045.27   272.8 1047.62   287.1 1050.51
   292.2 1052.43   296.1 1054.54   310.8 1064.13   315.6  1066.4   327.5 1070.95
   334.2 1074.66   351.2 1085.23   363.1 1091.17   384.5 1094.82   416.2 1098.49
#Mann= 3 ,-1,0
       0      .1       0  207.65    .045       0   222.3      .1       0
Bank Sta=207.65,222.3
XS Rating Curve= 0 ,0
Exp/Cntr(USF)=0,0
Exp/Cntr=0.3,0.1

Type RM Length L Ch R = 1 ,35400   ,203.3,194.8,189.8
XS GIS Cut Line= 6
1667206.24780442508214.464183673 1667280.2896511508264.388296425
1667341.08546126508309.6585470891667412.04332459508380.122316927
1667466.48744142508431.7048909221667529.99453226   508491.870453
#Sta/Elev= 30
       0 1121.08    13.5 1112.96    36.7  1100.9    76.1 1085.46   119.2 1064.59
     145 1050.63     152 1048.55   185.1 1043.58  192.881041.613   216.6  1040.3
  223.831041.612     227 1042.47     249 1042.39   251.9 1043.19   258.9 1047.96
   268.2 1058.26   273.7 1062.53     281 1066.69     288 1068.71   307.1 1071.99
   319.2 1072.14   328.5 1070.16   345.3 1063.79     350    1063   354.8 1064.05
   359.6 1066.47   383.4 1080.74     393 1085.43   407.5 1089.23   427.6 1091.52
#Mann= 7 ,-1,0
       0      .1       0    99.3     .06       0   185.1      .1       0
  192.88    .045       0  223.83      .1       0   255.1     .06       0
   315.1      .1       0
Bank Sta=192.88,223.83
XS Rating Curve= 0 ,0
Exp/Cntr(USF)=0,0
Exp/Cntr=0.3,0.1

Type RM Length L Ch R = 1 ,35205   ,103.1,105,106.1
XS GIS Cut Line= 2
1667078.52242563508444.6879044341667479.88854203508572.296153398
#Sta/Elev= 30
       0 1135.92    10.9 1132.83    17.8 1129.68    38.5 1121.73    52.2 1115.13
    62.6 1111.47    83.2 1100.68   100.4 1094.23     134 1078.56   151.6  1068.7
   162.4 1063.88   169.3 1059.56   173.2 1056.35   176.2 1052.35   179.6 1046.08
     183 1041.72   186.5 1040.12  196.921039.393   210.6  1038.3  222.821039.391
   241.6  1042.2   280.3 1044.53   296.7 1046.78   303.5 1048.61   313.9 1052.53
   341.4 1066.16   375.8 1078.76   386.2 1081.82   396.5 1084.11   421.2 1087.71
#Mann= 3 ,-1,0
       0      .1       0  196.92    .045       0  222.82      .1       0
Bank Sta=196.92,222.82
XS Rating Curve= 0 ,0
Exp/Cntr(USF)=0,0
Exp/Cntr=0.3,0.1

Type RM Length L Ch R = 1 ,35100   ,164.4,167.6,165.9
XS GIS Cut Line= 6
1667040.35706009508512.6811069251667119.10394984508550.902487174
1667187.44567667508581.7964542511667278.56754167508622.988629088
1667346.90894042508653.8829242591667429.00621717508684.695854753
#Sta/Elev= 30
       0 1132.43    13.9 1128.03    24.8  1121.9    35.7 1116.82      54 1109.43
    69.3 1101.82    91.4 1094.78   108.4 1087.22   145.9 1067.32   168.3  1058.6
   180.4 1050.36     184  1046.1   187.6  1042.9   191.2 1041.26   200.4 1038.61
   205.6 1037.62   223.6 1037.78  228.281038.609   232.7 1039.15   252.8 1039.36
   262.5 1040.23   284.7 1040.43   316.5 1042.86   326.9 1044.33   336.9 1048.53
   349.6 1055.96   366.8 1067.66   390.3 1079.38   400.5 1082.22   425.2 1086.61
#Mann= 3 ,-1,0
       0      .1       0   200.4    .045       0  228.28      .1       0
Bank Sta=200.4,228.28
XS Rating Curve= 0 ,0
Exp/Cntr(USF)=0,0
Exp/Cntr=0.3,0.1

Type RM Length L Ch R = 1 ,34932   ,231.6,243,233.9
XS GIS Cut Line= 3
1666970.67594705508583.7150691781667093.65103497508696.304808839
1667348.59268436508864.453216896
#Sta/Elev= 30
       0 1135.17    13.5 1131.53    26.9 1125.98      58 1104.75    66.9 1100.42
    83.1 1094.21   100.8 1084.22     111 1080.02   127.2  1067.4   143.5 1056.57
   151.4 1047.97   157.4 1044.22   172.9 1039.93   184.6  1037.9   212.2 1037.98
   228.9 1037.07   252.7 1038.24   267.2 1037.72  273.131036.591   286.8 1035.51
  293.02 1036.59   300.4 1041.99   313.5 1043.48   326.1 1047.67   337.9 1049.68
   361.5 1067.18   377.2 1075.68   383.8 1078.14   419.6 1085.02   472.1 1091.23
#Mann= 4 ,-1,0
       0     .08       0     100      .1       0  273.13    .045       0
  293.02      .1       0
Bank Sta=273.13,293.02
XS Rating Curve= 0 ,0
Exp/Cntr(USF)=0,0
Exp/Cntr=0.3,0.1

Type RM Length L Ch R = 1 ,34689   ,247.7,242.4,231.3
XS GIS Cut Line= 3
1666870.79480315508689.1121165351667131.48731429508908.521921152
1667225.26745142 508977.69395642
#Sta/Elev= 30
       0 1124.66    30.5 1117.98    36.4 1116.12    53.8 1106.17     119 1072.74
   140.8 1063.95   144.6 1061.77   147.9 1059.04   160.9 1044.09   166.2 1039.83
   169.3 1038.18   177.9 1036.03   191.2 1035.07   201.81033.001   216.8 1031.69
  222.361033.002   227.4 1035.54   233.6 1036.93   237.9 1037.24   246.5 1035.28
   252.8 1034.96   293.7 1040.28     303  1043.2   344.9 1066.01   355.9 1071.19
     366 1074.85   382.4 1079.61   414.2 1086.12   434.6 1089.12   457.3 1091.11
#Mann= 4 ,-1,0
       0      .1       0     110     .08       0   201.8    .045       0
  222.36     .08       0
Bank Sta=201.8,222.36
XS Rating Curve= 0 ,0
Exp/Cntr(USF)=0,0
Exp/Cntr=0.3,0.1

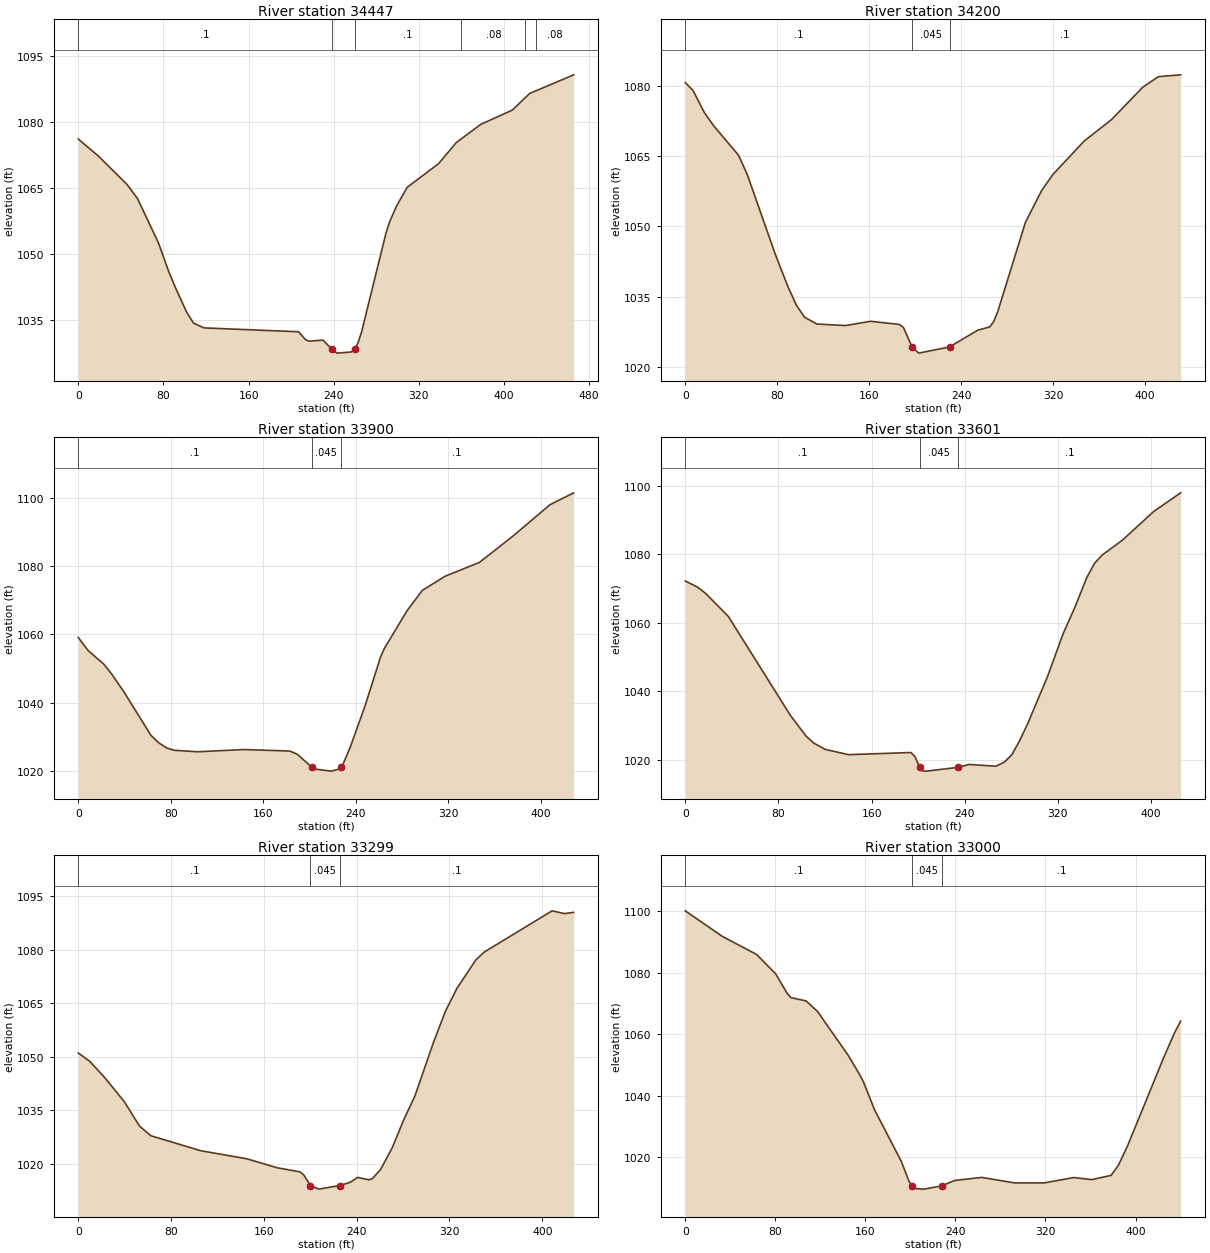
Type RM Length L Ch R = 1 ,34447   ,252,247.1,240.7
XS GIS Cut Line= 2
1666744.78583222509076.1948485731667208.83472308509039.242596121
#Sta/Elev= 30
       0 1076.17    19.1 1072.25    45.7 1065.85    55.6 1062.64    75.3 1052.52
    85.2 1045.83    91.8 1042.03     102 1036.64   108.3 1034.21   118.1 1033.14
     207 1032.26   213.6 1030.43   216.9 1030.12     230 1030.35  238.331028.273
   243.2 1027.39   256.4 1027.65  259.731028.275     263 1029.83   266.2 1032.22
   289.3 1054.91   292.6 1057.34   299.1 1060.93     309 1065.16   338.6 1070.58
   355.1 1075.35   378.1 1079.51   407.8 1082.77   424.2 1086.57   465.5 1090.81
#Mann= 6 ,-1,0
       0      .1       0  238.33    .045       0  259.73      .1       0
     360     .08       0     420      .1       0     430     .08       0
Bank Sta=238.33,259.73
XS Rating Curve= 0 ,0
Exp/Cntr(USF)=0,0
Exp/Cntr=0.3,0.1

Type RM Length L Ch R = 1 ,34200   ,293.9,299.8,302.6
XS GIS Cut Line= 6
1666820.24168667509385.9611845021666900.20018817509350.423854008
1666968.73581226509319.9632849991667060.27171843509279.697617501
1667134.40116334  509256.96144251667222.61653809509234.743639171
#Sta/Elev= 30
       0 1080.67     6.8 1078.97    16.6 1074.28    24.8 1071.43    46.3  1065.2
    53.9  1061.1    78.6 1043.89    89.4 1037.14    96.6 1033.27   103.7 1030.67
   114.5 1029.21   139.6 1028.89   161.2  1029.8   186.3 1029.12   189.9 1028.44
   197.31024.326   203.1 1023.01  229.941024.326   254.4 1027.89     265 1028.61
   268.4 1029.75   271.9 1031.87   295.9 1050.84   310.1 1057.67   319.9  1061.1
     347 1068.19     371 1072.81     398 1079.67   411.6 1081.93     431 1082.32
#Mann= 3 ,-1,0
       0      .1       0   197.3    .045       0  229.94      .1       0
Bank Sta=197.3,229.94
XS Rating Curve= 0 ,0
Exp/Cntr(USF)=0,0
Exp/Cntr=0.3,0.1

Type RM Length L Ch R = 1 ,33900   ,300.5,299,295
XS GIS Cut Line= 6
1666939.63383634509598.3209960011667027.12250651509574.791515499
1667101.77327584509563.0123395921667201.71992634509559.746270001
1667276.70960575509557.307298511  1667364.198604509554.477907836
#Sta/Elev= 30
       0 1059.05     8.5 1055.23    22.1 1051.23    28.9 1048.34    39.1 1043.31
    62.9 1030.38    69.7 1028.17    76.5 1026.69    83.2    1026   103.3 1025.57
   143.2 1026.22   182.9 1025.79   189.4 1024.88  202.161021.028   205.8 1020.46
     219  1019.9   225.5 1020.48  226.931021.026   229.2 1021.99   235.4 1026.97
   248.3 1039.17   261.6 1053.39   264.9 1055.88   284.6 1066.96   297.7 1072.86
   317.4    1077   347.2 1081.07   376.5 1088.87   408.2 1097.97   428.7 1101.45
#Mann= 3 ,-1,0
       0      .1       0  202.16    .045       0  226.93      .1       0
Bank Sta=202.16,226.93
XS Rating Curve= 0 ,0
Exp/Cntr(USF)=0,0
Exp/Cntr=0.3,0.1

Type RM Length L Ch R = 1 ,33601   ,298.5,302.5,308.4
XS GIS Cut Line= 6
1666944.15646508 509896.886999921667030.36232942509881.894575834
1667104.25325775509869.0438797621667202.40857325509849.806385428
1667275.56426685509832.7289917621667360.68614385509811.502984345
#Sta/Elev= 30
       0 1072.23    10.4 1070.47    17.1 1068.74      37 1061.87    90.3 1032.96
   103.6 1026.98   110.3 1024.88   120.3 1023.01   140.3 1021.49   193.7 1022.12
     197 1021.05  201.461017.796   203.7 1016.71   207.1 1016.68  234.521017.796
   243.8 1018.63   266.8 1018.12     274 1019.32   280.5 1021.48   287.5 1025.82
   294.1 1030.58   311.1 1044.33   324.5 1056.86   334.7 1064.63   344.8 1073.24
   351.5 1077.43   358.3  1079.9   375.2 1084.11   402.3 1092.56   425.4    1098
#Mann= 3 ,-1,0
       0      .1       0  201.46    .045       0  234.52      .1       0
Bank Sta=201.46,234.52
XS Rating Curve= 0 ,0
Exp/Cntr(USF)=0,0
Exp/Cntr=0.3,0.1

Type RM Length L Ch R = 1 ,33299   ,301.4,298.5,291.1
XS GIS Cut Line= 5
1666931.41633309510127.5302394181667018.53426909510135.697545916
   1667093.20702510142.6978600031667197.32406061510155.557778328
1667356.87011809510148.064485269
#Sta/Elev= 30
       0 1051.06     9.9 1048.73    23.1 1044.06    39.6 1037.46    52.8 1030.59
    62.6 1027.89   105.5 1023.71   145.2 1021.45   171.4 1018.93   191.2 1017.78
   194.5 1016.88  200.071013.959   207.4 1012.95  225.271013.959   234.2 1014.83
   240.8 1016.24   250.7 1015.55   253.5 1015.87   260.7 1018.48   270.6  1024.5
   280.4 1032.22   290.3 1039.09     306 1053.84   316.5 1062.74   326.4 1069.14
   342.8 1077.15   349.9 1079.31   408.5 1090.87     419 1090.09   427.1 1090.44
#Mann= 3 ,-1,0
       0      .1       0  200.07    .045       0  225.27      .1       0
Bank Sta=200.07,225.27
XS Rating Curve= 0 ,0
Exp/Cntr(USF)=0,0
Exp/Cntr=0.3,0.1

Type RM Length L Ch R = 1 ,33000   ,296.5,300.3,298.6
XS GIS Cut Line= 6
1666873.21795867510484.6312312481666958.10558417 510463.40981701
1667030.86626543510445.2198927551667128.69677842510420.602159843
1667208.27864026510415.3085352631667304.41197817510402.742943585
#Sta/Elev= 30
       0 1100.16      33 1091.82    63.4 1085.96    80.3 1079.66    90.5 1073.33
    93.8 1071.93   107.4 1070.83   117.5 1067.41   144.6 1053.21   154.7 1047.01
   158.1 1044.67   168.2 1035.39   191.9 1018.65   198.7 1012.24  201.451010.676
   205.5 1009.74   212.1  1009.6  228.081010.679   239.1  1012.4   263.4 1013.41
   292.6 1011.62   318.9 1011.62   345.2 1013.37   361.1 1012.69   378.3 1014.07
   384.9 1017.43     393 1023.73   425.5 1052.81   434.5 1060.33   440.1 1064.26
#Mann= 3 ,-1,0
       0      .1       0  201.45    .045       0  228.08      .1       0
Bank Sta=201.45,228.08
XS Rating Curve= 0 ,0
Exp/Cntr(USF)=0,0
Exp/Cntr=0.3,0.1

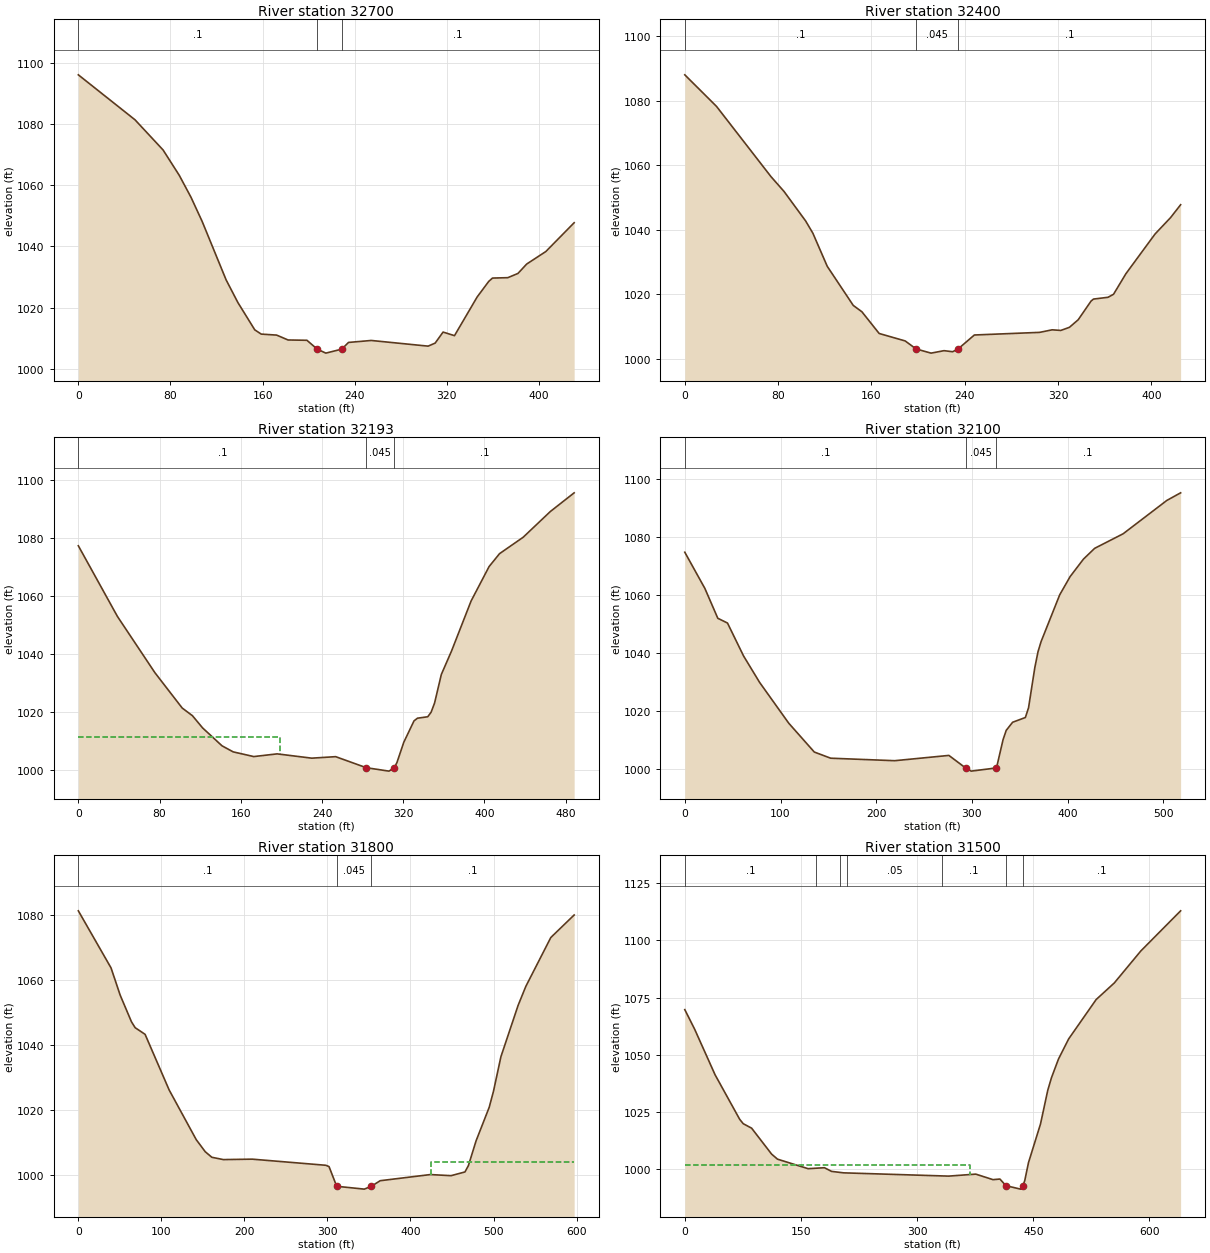
Type RM Length L Ch R = 1 ,32700   ,305.1,299.8,291.3
XS GIS Cut Line= 6
1667013.20094642510730.4745715861667097.86317867510699.529095426
1667172.14616659510680.3198162621667272.14367001 510678.93038334
1667347.22521275 510673.304082261667434.87726842510662.458303422
#Sta/Elev= 30
       0    1096    49.2 1081.33    73.6 1071.47    87.6 1063.23    97.8 1056.07
   107.5 1048.18   128.3 1029.11   138.5 1021.72   153.2 1012.78   158.8  1011.4
   172.2 1011.07   182.1 1009.48   198.5 1009.38  207.371006.494   214.9 1005.19
  228.731006.495   234.6 1008.68   254.3 1009.32   303.7 1007.47   309.8 1008.46
   316.7 1012.06   326.6 1010.89   346.3 1023.52   356.3 1028.58   359.6 1029.68
   372.9 1029.81   381.7 1031.19   389.3 1034.26   405.9 1038.34   430.5 1047.74
#Mann= 3 ,-1,0
       0      .1       0  207.37    .045       0  228.73      .1       0
Bank Sta=207.37,228.73
XS Rating Curve= 0 ,0
Exp/Cntr(USF)=0,0
Exp/Cntr=0.3,0.1

Type RM Length L Ch R = 1 ,32400   ,200.9,207,206.7
XS GIS Cut Line= 6
1667105.48389834511067.2022445951667182.95159118 511026.51269342
1667249.32088101510991.582645178   1667337.81283 510945.00826326
1667404.18179175510910.077558845 1667482.5428555510871.104211584
#Sta/Elev= 30
       0 1087.96    27.2 1078.19    73.9 1056.45    85.1 1051.86   103.6 1042.74
   109.8 1038.95   122.1 1028.72   144.4 1016.62   151.8 1014.66   166.6 1007.94
   188.9 1005.63  198.291003.145   211.1 1001.86   222.2 1002.62   229.6 1002.29
  234.241003.146   248.2 1007.47   304.1 1008.28   314.9 1009.07   322.3 1008.88
   329.7 1009.85   337.2 1012.18   348.2 1017.95   350.3 1018.58   362.8 1019.14
   367.5 1020.07   378.1 1026.43   403.1 1038.72   416.4 1043.79     425 1047.77
#Mann= 3 ,-1,0
       0      .1       0  198.29    .045       0  234.24      .1       0
Bank Sta=198.29,234.24
XS Rating Curve= 0 ,0
Exp/Cntr(USF)=0,0
Exp/Cntr=0.3,0.1

Type RM Length L Ch R = 1 ,32193   ,89.4,93,90.1
XS GIS Cut Line= 2
1667123.50510763511190.7118561731667600.56363837511086.662053171
#Sta/Elev= 30
       0  1077.3    38.5 1052.93    75.4 1033.53   102.3 1021.33   112.4 1018.68
   122.4 1014.47   141.5  1008.3   152.5 1006.21   172.8 1004.59   195.8 1005.52
   229.9 1004.04   253.4 1004.56   283.6 1000.75   305.9  999.57  311.241000.753
   313.8 1002.56   320.5 1009.51   330.6 1016.91     334 1017.83   344.1 1018.32
   347.4 1019.87   350.8 1023.01   357.5 1032.92   367.6 1041.05   386.8 1058.25
   404.5 1070.11   414.8 1074.57   438.1 1080.24   464.9 1089.13   488.3 1095.56
#Mann= 3 ,-1,0
       0      .1       0   283.6    .045       0  311.24      .1       0
#XS Ineff= 2 , 0
          198.19 1011.34
Permanent Ineff=
       F       F
Bank Sta=283.6,311.24
XS Rating Curve= 0 ,0
Exp/Cntr(USF)=0,0
Exp/Cntr=0.3,0.1

Type RM Length L Ch R = 1 ,32100   ,323.6,300,288
XS GIS Cut Line= 6
1667124.23510882511277.588840304  1667298.907396511236.930907756
1667372.79832435511224.0802116691667471.31912467511206.945731506
1667546.50040476511201.5300599191667634.75514951511200.411295757
#Sta/Elev= 30
       0  1074.7      21 1062.22    34.5 1051.95    44.6 1050.32    61.4 1038.98
    78.1 1029.91   108.6 1015.83   135.3  1005.9   152.4 1003.78   219.3 1002.92
   275.9 1004.74  293.481000.398   299.2  999.33  324.671000.398   325.9 1000.81
   332.5 1010.16   335.8 1013.37   342.5 1016.16   355.8 1017.79   359.1 1021.11
   365.7 1035.01     369 1040.42   372.2 1043.91   391.7 1060.05   402.6 1066.33
   416.5 1072.33   428.2 1076.04   457.9 1081.04   503.6 1092.53     518 1095.15
#Mann= 3 ,-1,0
       0      .1       0  293.48    .045       0  324.67      .1       0
Bank Sta=293.48,324.67
XS Rating Curve= 0 ,0
Exp/Cntr(USF)=0,0
Exp/Cntr=0.3,0.1

Type RM Length L Ch R = 1 ,31800   ,299.5,300,299.9
XS GIS Cut Line= 6
 1667317.1230279511787.8454807621667420.91797876511600.241532832
1667460.25681084511536.3866736741667512.70880568511451.246752083
  1667572.438345511374.8886370961667648.42506967511294.264782593
#Sta/Elev= 30
       0 1081.24    39.4 1063.67    50.4 1055.29      64 1047.09    68.4 1045.29
    80.4 1043.23   109.4  1026.1     142 1010.82   152.9 1007.09   160.8  1005.4
   174.6 1004.69   209.5 1004.82     298 1002.94   301.9 1002.54  311.12996.4734
   344.3   995.6  352.89996.4732   363.5  998.19   423.9 1000.08   448.9  999.74
   465.6 1000.89   469.7 1002.81     479 1010.46   494.8 1020.78   499.9 1025.66
   508.9 1036.35   529.6 1052.14   538.9 1057.99     569 1073.03   597.1 1079.96
#Mann= 3 ,-1,0
       0      .1       0  311.12    .045       0  352.89      .1       0
#XS Ineff= 2 , 0
                          424.12          1003.8
Permanent Ineff=
       F       F
Bank Sta=311.12,352.89
XS Rating Curve= 0 ,0
Exp/Cntr(USF)=0,0
Exp/Cntr=0.3,0.1

Type RM Length L Ch R = 1 ,31500   ,297.7,305.3,310.4
XS GIS Cut Line= 6
1667458.54040902511896.8215715721667654.02446793511665.663974166
 1667710.4305231511616.212629512 1667784.3496666511548.863354757
1667839.78951634511498.3516447541667904.46884893511439.420988336
#Sta/Elev= 30
       0 1069.71    12.7 1061.16    39.1 1041.22    70.9 1021.73    75.5 1019.82
    86.3 1017.87   112.1 1006.53   119.7 1004.32   159.2 1000.16   180.3 1000.58
   189.5  998.98     205  998.34   340.7  996.91   375.7  997.78     398  995.36
   406.9  995.63  414.62992.7333   433.5  991.22   436.8992.7361     439  995.05
   443.8 1002.84   459.3 1019.72   468.6 1034.37   473.4  1039.9   482.5  1048.1
   495.6 1056.88   531.1  1074.1   554.5 1081.35   588.8 1095.35   640.2 1112.91
#Mann= 7 ,-1,0
       0      .1       0     170     .05       0     200      .1       0
     210     .05       0  332.73      .1       0  414.62    .045       0
   436.8      .1       0
#XS Ineff= 2 , 0
          368.45  1001.9
Permanent Ineff=
       F       F
Bank Sta=414.62,436.8
XS Rating Curve= 0 ,0
Exp/Cntr(USF)=0,0
Exp/Cntr=0.3,0.1

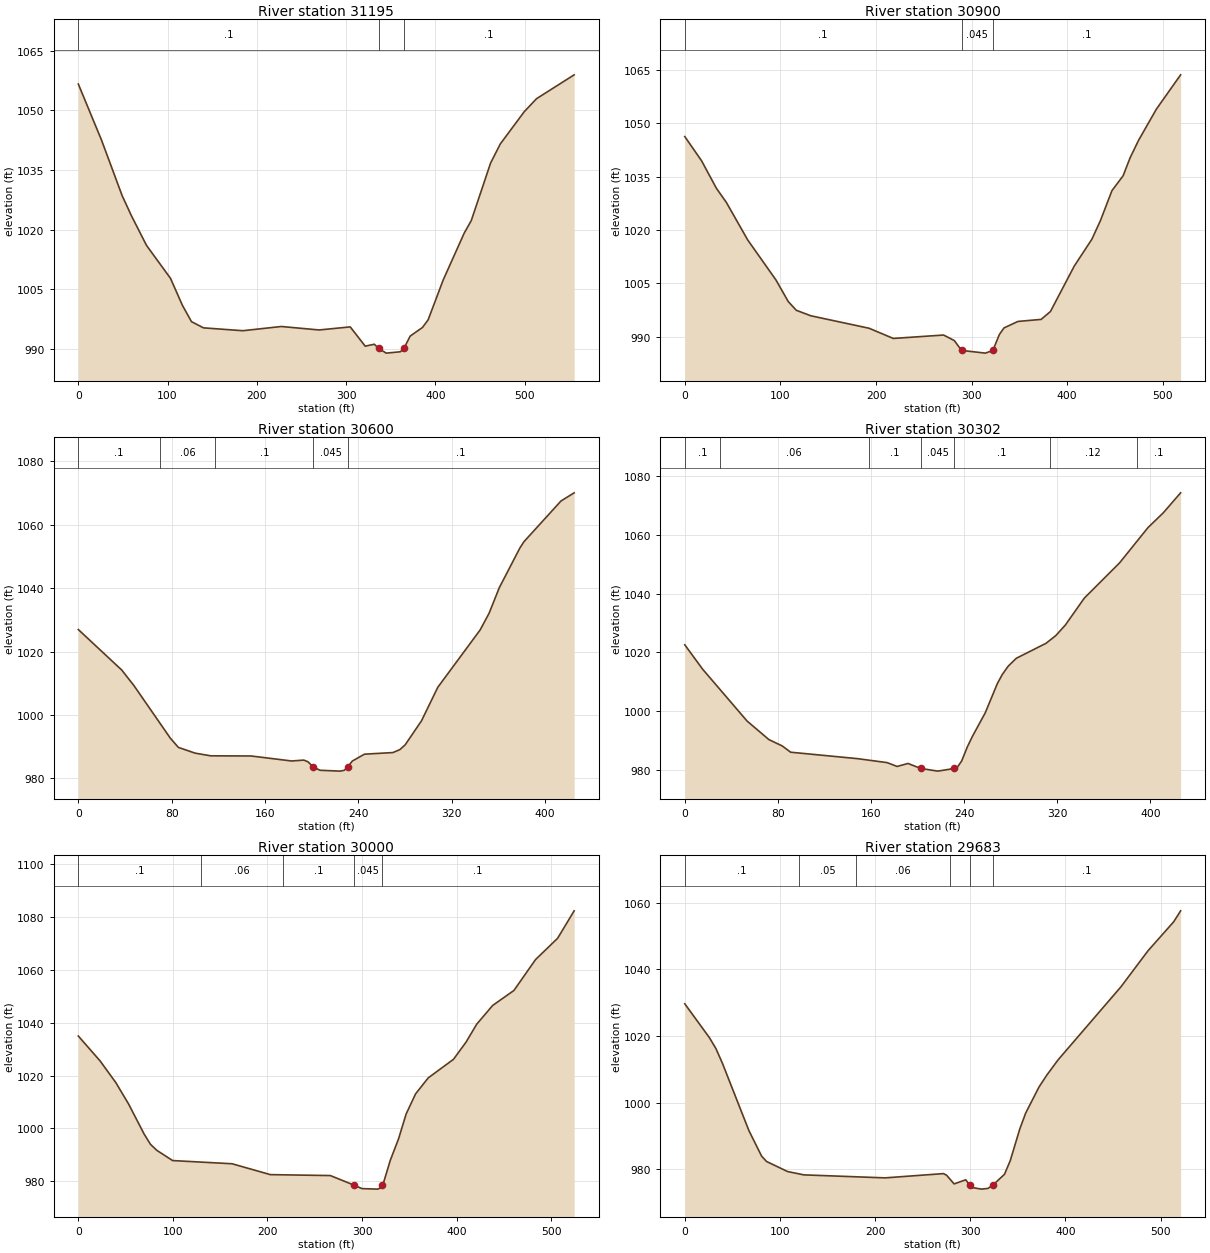
Type RM Length L Ch R = 1 ,31195   ,303.8,294.7,285.4
XS GIS Cut Line= 3
1667519.49576906511936.0701883051667912.12106459511850.828302011
1668061.67719052511814.769579088
#Sta/Elev= 30
       0 1056.65    26.1 1042.48    49.1 1028.57    59.6 1023.47    76.4 1016.06
   103.3 1007.76   116.7 1000.95   126.8  996.87   140.2  995.31   184.3  994.59
   227.5  995.65   269.8  994.78   304.7  995.55   321.5   990.7   331.6  991.19
  336.72990.1208     345  988.95   360.8  989.29  364.84990.1207   371.8  993.22
   385.7  995.42     392  997.34   408.8 1007.33   432.4 1019.15   440.3 1022.29
     462  1036.8   472.9  1041.6   499.6 1049.67   513.4 1052.96   555.6 1058.97
#Mann= 3 ,-1,0
       0      .1       0  336.72    .045       0  364.84      .1       0
Bank Sta=336.72,364.84
XS Rating Curve= 0 ,0
Exp/Cntr(USF)=0,0
Exp/Cntr=0.3,0.1

Type RM Length L Ch R = 1 ,30900   ,304.8,300,292.4
XS GIS Cut Line= 5
1667776.01562941 512304.521223061667974.68983708512142.991759673
1668042.26220851512069.2763559221668092.94156909 512013.98972109
1668152.06743509511949.488537759
#Sta/Elev= 30
       0 1046.32    17.5 1039.54    33.1 1031.76    43.5 1027.79    65.8 1017.25
    95.4 1005.97   108.1  999.96   116.6  997.46   131.9  995.91   192.7  992.41
   218.1  989.54   270.7   990.5   281.9  988.94  289.47 986.177   314.4  985.41
  322.27986.1766     329  990.63   333.8  992.49   348.4  994.32   372.7   994.9
   382.4   997.1   407.3 1009.87   425.8 1017.46   434.7 1022.67   446.8 1031.13
   458.4 1035.27   465.8 1040.38   474.6 1045.26   493.2 1054.02   518.6 1063.69
#Mann= 3 ,-1,0
       0      .1       0  289.47    .045       0  322.27      .1       0
Bank Sta=289.47,322.27
XS Rating Curve= 0 ,0
Exp/Cntr(USF)=0,0
Exp/Cntr=0.3,0.1

Type RM Length L Ch R = 1 ,30600   ,293.7,298,304.7
XS GIS Cut Line= 6
1668174.76948942 512489.52059418 1668203.0925955512406.731389672
1668227.36879367512335.7689331771668259.73847958512241.152652591
1668286.06552668512170.8919663431668318.15010817512089.389504671
#Sta/Elev= 30
       0 1026.93    37.3 1014.12    47.7 1009.23    78.9  992.63    85.8  989.73
   100.2  987.91   113.6  987.07   148.2  987.02   182.9  985.44   193.3  985.72
   196.8  985.21  201.48983.5364   207.2  982.51   224.5  982.24     228   982.5
  230.81 983.534   234.9  985.42   245.3  987.59   269.7   988.1   275.7  989.04
   280.2  990.53   294.2  998.11   308.2 1008.71   344.5 1026.81   352.1 1032.02
   360.9 1040.13   378.5 1052.63   382.1 1054.68   413.8 1067.51   425.1 1070.09
#Mann= 5 ,-1,0
       0      .1       0      70     .06       0   117.5      .1       0
  201.48    .045       0  230.81      .1       0
Bank Sta=201.48,230.81
XS Rating Curve= 0 ,0
Exp/Cntr(USF)=0,0
Exp/Cntr=0.3,0.1

Type RM Length L Ch R = 1 ,30302   ,308.4,302,293.1
XS GIS Cut Line= 6
1668344.85248259512596.7562720921668407.60498175  512535.1044925
1668461.06386434512481.779467925 1668526.1470675512405.748452008
1668572.56200093512346.8358401661668626.71445167512278.106318846
#Sta/Elev= 30
       0 1022.55    15.4 1014.23    53.5  996.64    72.3  990.32    83.7  988.17
      91  986.03   148.5  983.84   173.8   982.5   182.5  981.19   191.8  982.21
  202.77980.5104   217.4   979.6   231.7  980.51   234.3  980.95     238  983.11
   242.9  987.93   247.2  991.44   258.2  999.43   268.6 1009.37   272.8 1012.43
   277.9 1015.28   284.9 1017.98   310.4 1023.06   318.8 1025.68     327 1029.26
   343.3 1038.42   373.7 1050.45   398.1 1062.44   411.1  1067.4   426.1 1074.24
#Mann= 7 ,-1,0
       0      .1       0      30     .06       0  157.97      .1       0
  202.77    .045       0   231.7      .1       0  313.56     .12       0
  388.56      .1       0
Bank Sta=202.77,231.7
XS Rating Curve= 0 ,0
Exp/Cntr(USF)=0,0
Exp/Cntr=0.3,0.1

Type RM Length L Ch R = 1 ,30000   ,313.8,316.5,315.4
XS GIS Cut Line= 6
1668710.38452321512854.1172606821668743.99636935512670.371610418
1668757.81819209512596.6562066671668776.24728909512498.369001672
1668790.06878376512424.6535979211668806.19440767512338.652129501
#Sta/Elev= 30
       0 1034.94      23 1025.54    39.6 1017.36      53 1009.35    69.5  997.94
    76.3  993.99      83  991.73    99.7  987.86   162.6  986.65   203.1  982.54
   266.5  982.19  291.14978.6257   299.9  977.26   316.6  977.06   319.9  977.55
   321.4978.6271   323.2  980.04   329.9  987.98   338.6  996.05   346.6 1005.43
   356.6 1013.07     370 1019.12   396.7 1026.14   410.1  1032.7   421.2 1039.39
   438.1  1046.5   460.6 1052.17   483.5 1063.86   506.8 1071.89   524.3 1082.28
#Mann= 5 ,-1,0
       0      .1       0     130     .06       0  216.79      .1       0
  291.14    .045       0   321.4      .1       0
Bank Sta=291.14,321.4
XS Rating Curve= 0 ,0
Exp/Cntr(USF)=0,0
Exp/Cntr=0.3,0.1

Type RM Length L Ch R = 1 ,29683   ,152.8,179.7,208.6
XS GIS Cut Line= 5
1668975.71096894512964.7054423131669048.11046173512716.754539893
1669067.72197107 512618.696337061669082.43060307512545.152848974
1669105.49190866512460.546390892
#Sta/Elev= 30
       0 1029.65    25.9 1019.48    32.8 1016.17    39.6 1011.76    67.4  991.57
    80.7  983.94    85.9  982.32     108   979.3   125.1   978.3   210.5   977.4
   271.8  978.68   275.1  978.19     283  975.59   295.2  976.82  299.39975.2376
   301.8   974.5   311.9  974.02   318.6  974.24  323.75975.2369   335.9  978.46
     342  982.59     352  992.07   358.2  996.86   372.1 1004.63   380.3 1008.21
   392.2 1012.82   458.3 1034.76   486.7 1045.57   513.7 1054.27     521 1057.57
#Mann= 6 ,-1,0
       0      .1       0     120     .05       0     180     .06       0
   278.3      .1       0  299.39    .045       0  323.75      .1       0
Bank Sta=299.39,323.75
XS Rating Curve= 0 ,0
Exp/Cntr(USF)=0,0
Exp/Cntr=0.3,0.1