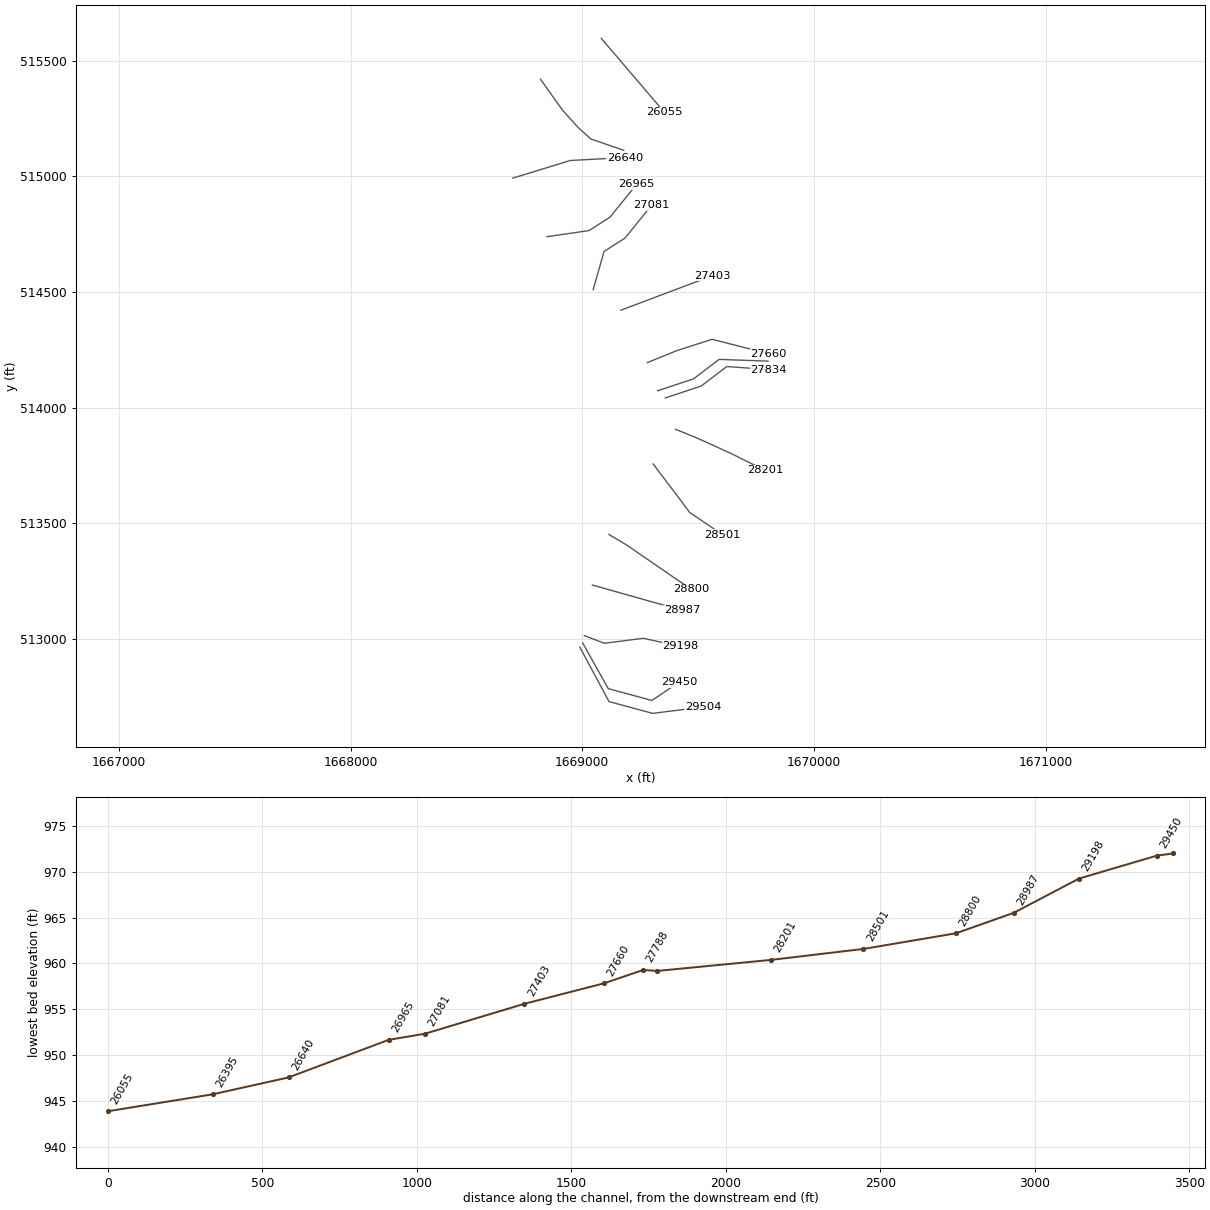
HEC-RAS study WlfRn.prj: WlfRn

--- WlfRn.g01 (geometry) --- (continued)

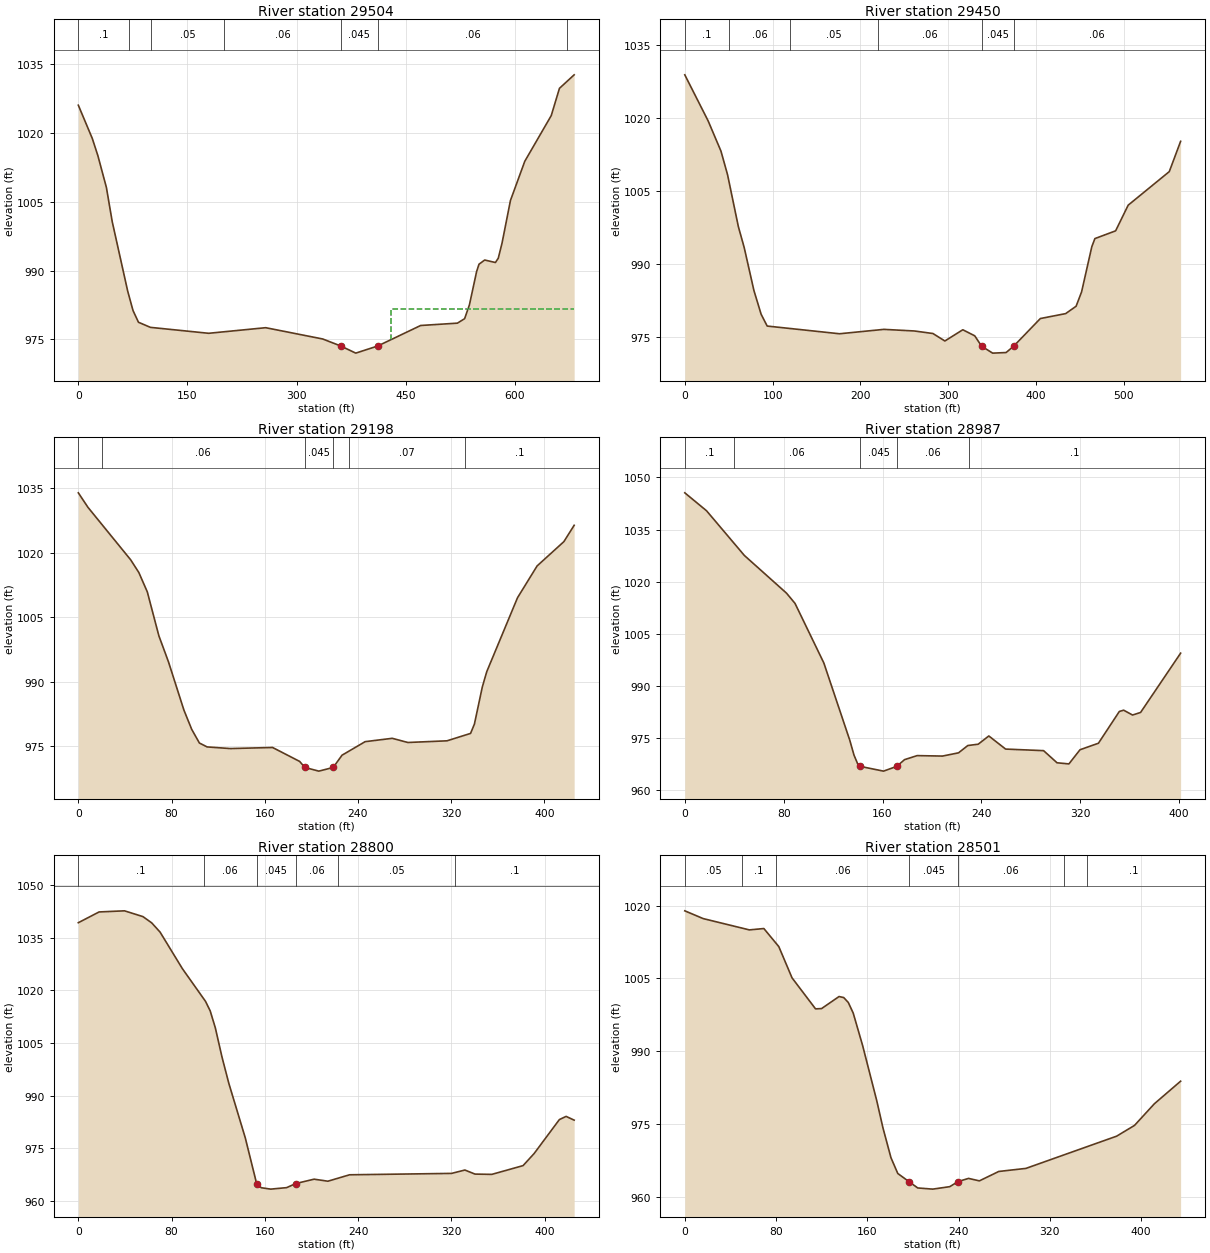
Type RM Length L Ch R = 1 ,29504   ,53.2,53.6,55.5
XS GIS Cut Line= 4
1668989.47927026512963.4803295661669115.43009485512728.248389077
1669303.91719702512677.1685927641669521.75483815512704.738417284
#Sta/Elev= 30
       0 1026.01    19.2 1018.77    26.9 1015.01    38.6 1008.09    46.6 1000.65
    67.8  985.56    75.2  981.28    82.7  978.73    99.2  977.62   179.2  976.33
   257.6  977.55     336  975.09  360.98 973.553   381.4  972.01  411.47 973.553
   470.7  978.03   521.2  978.54   531.1  979.51   537.7  982.52   547.6  989.79
   550.9  991.38   558.7  992.29   573.4  991.75   577.4  992.69   582.6  996.01
   594.1 1005.25   613.8 1013.79   650.2 1023.75   661.5 1029.69   681.7 1032.63
#Mann= 7 ,-1,0
       0      .1       0      70     .06       0     100     .05       0
     200     .06       0  360.98    .045       0  411.47     .06       0
  672.11      .1       0
#XS Ineff= 2 , 0
                           429.6          981.73
Permanent Ineff=
       F       F
Bank Sta=360.98,411.47
XS Rating Curve= 0 ,0
Exp/Cntr(USF)=0,0
Exp/Cntr=0.3,0.1

Type RM Length L Ch R = 1 ,29450   ,242.5,252.1,256.4
XS GIS Cut Line= 4
1669001.40828199512982.2999553891669112.08974345512784.150753915
1669300.57684562512733.0709576011669418.55769934512812.508142573
#Sta/Elev= 30
       0 1028.82    26.6 1019.37    41.2 1013.17    48.7 1008.33      61  997.69
    67.6  993.44    78.7   984.6    86.9  979.74    93.8  977.32   176.1  975.74
   226.7  976.64   261.4  976.31   282.5  975.79   296.1  974.26   316.5  976.56
   330.1  975.32  337.92 973.189   350.5  971.77   365.8  971.89   374.4973.1887
   404.8  978.86   433.6  979.87   445.5  981.38   451.7  984.29   463.4  993.59
   466.9  995.25   490.5  996.84   504.8  1002.1   551.6 1008.98   564.5 1015.19
#Mann= 6 ,-1,0
       0      .1       0      50     .06       0     120     .05       0
     220     .06       0  337.92    .045       0   374.4     .06       0
Bank Sta=337.92,374.4
XS Rating Curve= 0 ,0
Exp/Cntr(USF)=0,0
Exp/Cntr=0.3,0.1

Type RM Length L Ch R = 1 ,29198   ,211.7,211.2,202.7
XS GIS Cut Line= 4
1669009.01453293513013.6803872581669094.77904728512980.460838721
1669263.17953196513002.0126314991669423.10221015512966.908229887
#Sta/Elev= 30
       0 1033.89     8.3 1030.51    44.9 1018.34    51.9  1015.4    59.2 1010.88
    69.1  1000.7    77.4  994.61    90.6  983.44    97.3  978.96   103.9  975.79
   110.5  974.88   130.4   974.5   166.7  974.75   189.9  971.52   194.4  970.11
   206.4  969.26   218.7  970.11   226.3  972.96   246.1   976.1   269.4  976.88
   282.8  975.91   316.4   976.3   336.6  978.02   339.9  980.18   346.7  988.82
   350.5  992.36   376.9 1009.53   393.7 1016.91   416.7 1022.56   425.5 1026.35
#Mann= 6 ,-1,0
       0      .1       0      20     .06       0   194.4    .045       0
   218.7     .06       0  231.97     .07       0  331.75      .1       0
Bank Sta=194.4,218.7
XS Rating Curve= 0 ,0
Exp/Cntr(USF)=0,0
Exp/Cntr=0.3,0.1

Type RM Length L Ch R = 1 ,28987   ,191.1,186.8,180.7
XS GIS Cut Line= 2
1669043.78518865513232.3881256081669429.78319825 513123.17163452
#Sta/Elev= 30
       0 1045.55    17.6 1040.39    48.2 1027.54    82.3  1016.7    89.2 1013.75
   112.5  996.63   133.5   974.4   136.9  970.13   140.3  967.27  141.93966.8817
   160.8  965.52  171.48966.8833   177.8  968.82     188  969.98   208.5  969.85
   221.5  970.78     229  972.88   237.4  973.26     246  975.63   259.6  971.86
   290.3  971.41   301.2  967.92   310.8  967.59   319.8  971.67   334.7  973.54
   351.6  982.67   355.1  983.05   362.3  981.65   368.8  982.39   401.2  999.44
#Mann= 5 ,-1,0
       0      .1       0      40     .06       0  141.93    .045       0
  171.48     .06       0     230      .1       0
Bank Sta=141.93,171.48
XS Rating Curve= 0 ,0
Exp/Cntr(USF)=0,0
Exp/Cntr=0.3,0.1

Type RM Length L Ch R = 1 ,28800   ,299.7,299.6,285.2
XS GIS Cut Line= 6
1669115.20803845513450.817813463 1669190.6832812513406.142705969
 1669252.4548112513363.607029877 1669334.8168512513306.892904467
1669396.58870928513264.3578845481669468.65582237513214.733639963
#Sta/Elev= 30
       0 1039.33    17.8  1042.4    39.6 1042.72    55.4 1041.07    62.9 1039.29
    70.1 1036.65    89.2 1026.23   109.1 1016.87   113.1 1014.15   117.5  1009.3
   123.2 1000.99     129  993.55   143.2  977.89  152.88964.8926   156.9  963.69
   164.9  963.29   178.6  963.71  186.61964.8958   202.2  966.13     214  965.55
   232.6  967.38   320.1  967.78   331.5  968.74   340.2  967.58   354.6   967.5
   381.4     970   390.9  973.46   412.5  983.13   418.3  984.05   425.2  982.98
#Mann= 6 ,-1,0
       0      .1       0  107.71     .06       0  152.88    .045       0
  186.61     .06       0  222.71     .05       0  322.71      .1       0
Bank Sta=152.88,186.61
XS Rating Curve= 0 ,0
Exp/Cntr(USF)=0,0
Exp/Cntr=0.3,0.1

Type RM Length L Ch R = 1 ,28501   ,286.8,300,309.7
XS GIS Cut Line= 5
1669306.01361801513756.4931258411669358.39835575513686.401730582
1669403.87365851513626.7611018421669463.58154434513546.534556255
 1669605.9231074513449.748087283
#Sta/Elev= 30
       0 1018.92    16.1 1017.32    56.6 1014.99    69.3 1015.27    82.4 1011.55
      94 1005.11   114.6  998.72   119.9  998.78   135.2 1001.26   139.3 1001.05
   143.3 1000.04   147.6  997.87   155.9  991.14   168.2  979.85   173.7  974.19
   180.7  968.06   186.7   964.8  196.45963.1348   204.2  961.82   217.3  961.58
   232.3  962.09  239.52963.1347   248.7  963.79   258.2  963.28   275.2  965.22
     299  965.85   378.5  972.49   394.2  974.71   411.6  979.17   434.6  983.82
#Mann= 7 ,-1,0
       0     .05       0      50      .1       0      80     .06       0
  196.45    .045       0  239.52     .06       0  332.51     .05       0
  352.51      .1       0
Bank Sta=196.45,239.52
XS Rating Curve= 0 ,0
Exp/Cntr(USF)=0,0
Exp/Cntr=0.3,0.1

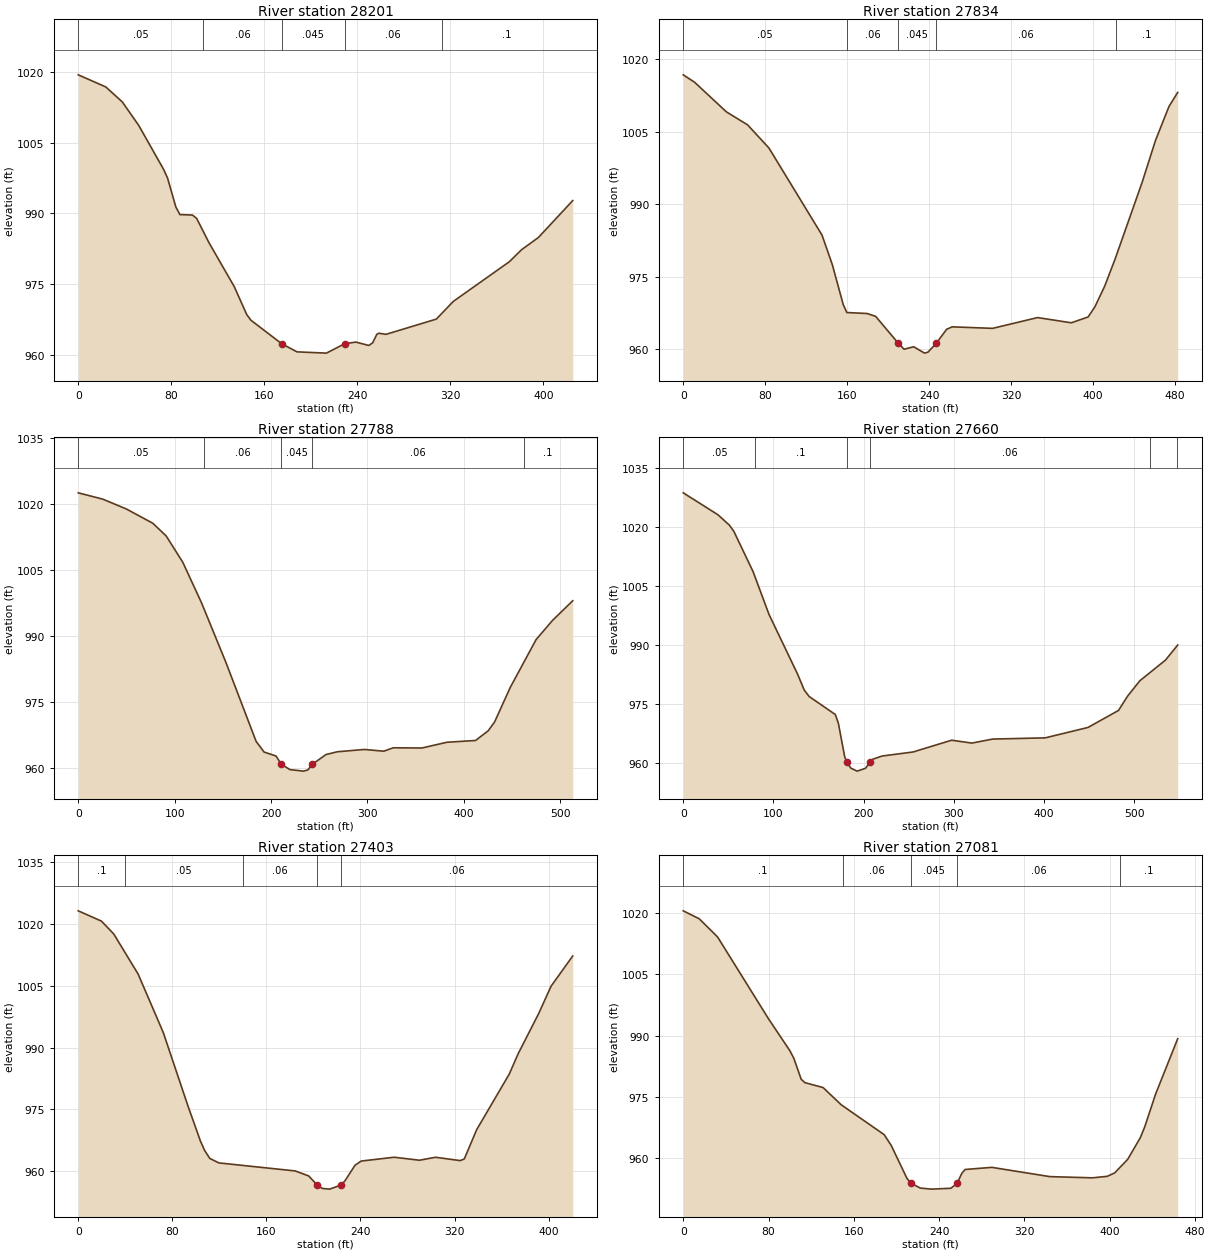
Type RM Length L Ch R = 1 ,28201   ,334,366.9,370.1
XS GIS Cut Line= 6
1669402.83133775513905.9409896731669484.04803884513873.227800503
1669552.55840051513842.7101450121669643.41058101513800.909047499
1669710.62140459513767.473418832 1669789.2629796513728.980385587
#Sta/Elev= 30
       0 1019.36    23.7 1016.79    37.9 1013.61      52 1008.64    73.3  999.36
    76.8  997.48    83.9  991.36    87.4  989.74    98.2  989.64   101.8  988.94
   112.5  983.74   134.1  974.49   144.9  968.54   148.5  967.35  174.97962.3643
   188.1  960.65   213.4  960.38  229.07962.3676   238.7  962.72   249.8  962.01
   253.1  962.54   256.7  964.35   258.4   964.6   264.6  964.36   307.9  967.59
   322.6  971.36   370.7  979.75   381.1  982.28   395.7  984.89   425.2  992.71
#Mann= 5 ,-1,0
       0     .05       0  107.56     .06       0  174.97    .045       0
  229.07     .06       0  312.56      .1       0
Bank Sta=174.97,229.07
XS Rating Curve= 0 ,0
Exp/Cntr(USF)=0,0
Exp/Cntr=0.3,0.1

Type RM Length L Ch R = 1 ,27834   ,45.5,46.1,46.5
XS GIS Cut Line= 4
1669358.62181608514041.9576852521669513.55833452514093.356276854
1669623.83562266 514177.702767651669804.06144923514164.745209162
#Sta/Elev= 30
       0  1016.8      11 1015.28    42.1 1009.14    62.9 1006.43    83.7 1001.64
   135.5  983.62   145.5  977.55   156.2  969.25   159.7  967.59   179.6  967.38
   187.9  966.79  210.02961.2153   215.6  959.99     225   960.5   235.6  959.18
     239  959.39  247.04961.2133   257.2  964.12   262.6  964.62   302.1  964.31
     346  966.54   378.9  965.46   395.3  966.66   401.9  968.75   411.5  973.04
   421.6  978.62     448   994.5   461.1 1003.21   474.3 1010.26   482.8 1013.16
#Mann= 5 ,-1,0
       0     .05       0     160     .06       0  210.02    .045       0
  247.04     .06       0  422.08      .1       0
Bank Sta=210.02,247.04
XS Rating Curve= 0 ,0
Exp/Cntr(USF)=0,0
Exp/Cntr=0.3,0.1

Type RM Length L Ch R = 1 ,27788   ,128.8,127.1,121.1
XS GIS Cut Line= 4
1669325.19458497514072.8625946941669480.13110341514124.261186296
1669590.40839155514208.6076770921669801.17294437514201.103462577
#Sta/Elev= 30
       0 1022.49    25.5 1021.05    49.7 1018.84    77.3 1015.59    91.2  1012.7
   108.5  1006.7     128  997.45   153.4  983.86   184.5  966.05   192.8  963.61
   205.2  962.71   210.7960.8235   219.7  959.62   233.7  959.28   238.2  959.55
  242.72960.8245   257.1  963.05   268.8  963.68   296.9   964.2     317  963.81
   326.8  964.58   356.4  964.53   382.6  965.84   412.2  966.24   425.3  968.44
   431.9  970.43   448.3  978.34     475  989.16     492  993.51     513  997.98
#Mann= 5 ,-1,0
       0     .05       0     130     .06       0   210.7    .045       0
  242.72     .06       0  462.08      .1       0
Bank Sta=210.7,242.72
XS Rating Curve= 0 ,0
Exp/Cntr(USF)=0,0
Exp/Cntr=0.3,0.1

Type RM Length L Ch R = 1 ,27660   ,253.6,257.1,254.8
XS GIS Cut Line= 4
1669281.02058801514194.6240436021669405.41784754514245.457060875
1669560.50747023514295.5264368711669803.38645784514233.434852792
#Sta/Elev= 30
       0 1028.67    38.4  1023.1    51.2 1020.43    56.1 1018.86    77.4 1008.61
    95.1  997.69   126.7  982.53   134.1  978.46   139.5  976.83   168.6  972.22
     172  969.93   178.9  961.53  181.32 960.044   185.8  958.58   192.7  957.82
     202  958.54  206.85 960.045   209.8  960.83   220.3  961.66   254.8   962.7
   297.4  965.69   319.9  964.96   342.9  965.98   401.2  966.29   448.6  968.94
   482.4  973.27   492.6  976.96   506.1  980.84   534.4  986.08     548  989.92
#Mann= 6 ,-1,0
       0     .05       0      80      .1       0  181.32    .045       0
  206.85     .06       0  517.35      .1       0  547.35     .07       0
Bank Sta=181.32,206.85
XS Rating Curve= 0 ,0
Exp/Cntr(USF)=0,0
Exp/Cntr=0.3,0.1

Type RM Length L Ch R = 1 ,27403   ,317,322,314.3
XS GIS Cut Line= 2
1669166.93360153514421.5286973811669560.29875444514570.156328279
#Sta/Elev= 30
       0 1023.21    19.7 1020.71    30.2 1017.58    50.9 1007.85    72.3  993.64
    93.3  975.79   103.9  967.27   107.4  965.02   111.9  963.04   119.6  961.96
   184.5  960.01   195.9   958.8  203.33  956.56   207.6  955.76   213.8  955.59
   223.1  956.55   226.6  957.52   235.4  961.41   240.6  962.41   268.7  963.34
   290.1  962.61   303.8  963.33   324.8  962.52   328.3  962.93   338.8  970.03
   366.5  983.53   374.1  988.49   391.5  998.23   402.1 1004.91   420.5 1012.24
#Mann= 5 ,-1,0
       0      .1       0      40     .05       0     140     .06       0
  203.33    .045       0   223.1     .06       0
Bank Sta=203.33,223.1
XS Rating Curve= 0 ,0
Exp/Cntr(USF)=0,0
Exp/Cntr=0.3,0.1

Type RM Length L Ch R = 1 ,27081   ,115.4,116.6,114.9
XS GIS Cut Line= 4
1669046.90145749514509.8537129211669093.94707965514675.544507344
1669184.69774314514733.6316072791669300.13507699514876.503724242
#Sta/Elev= 30
       0 1020.59      15 1018.64    32.2 1014.18      80  994.09     100  986.28
   103.8  984.36   110.6  979.28   114.1  978.44   131.1  977.24   148.2     973
   188.4  965.69   195.1  963.01   209.8  954.96  213.75953.7513   222.3  952.58
   232.7  952.32     251  952.53  256.87953.7516   261.3  956.23   264.4  957.14
   289.4  957.66   343.7  955.39   383.7  955.09   397.6  955.46   404.6   956.3
   416.8  959.63   428.6  964.92   432.8  967.61   442.9  975.59   463.7  989.22
#Mann= 5 ,-1,0
       0      .1       0     150     .06       0  213.75    .045       0
  256.87     .06       0  409.99      .1       0
Bank Sta=213.75,256.87
XS Rating Curve= 0 ,0
Exp/Cntr(USF)=0,0
Exp/Cntr=0.3,0.1

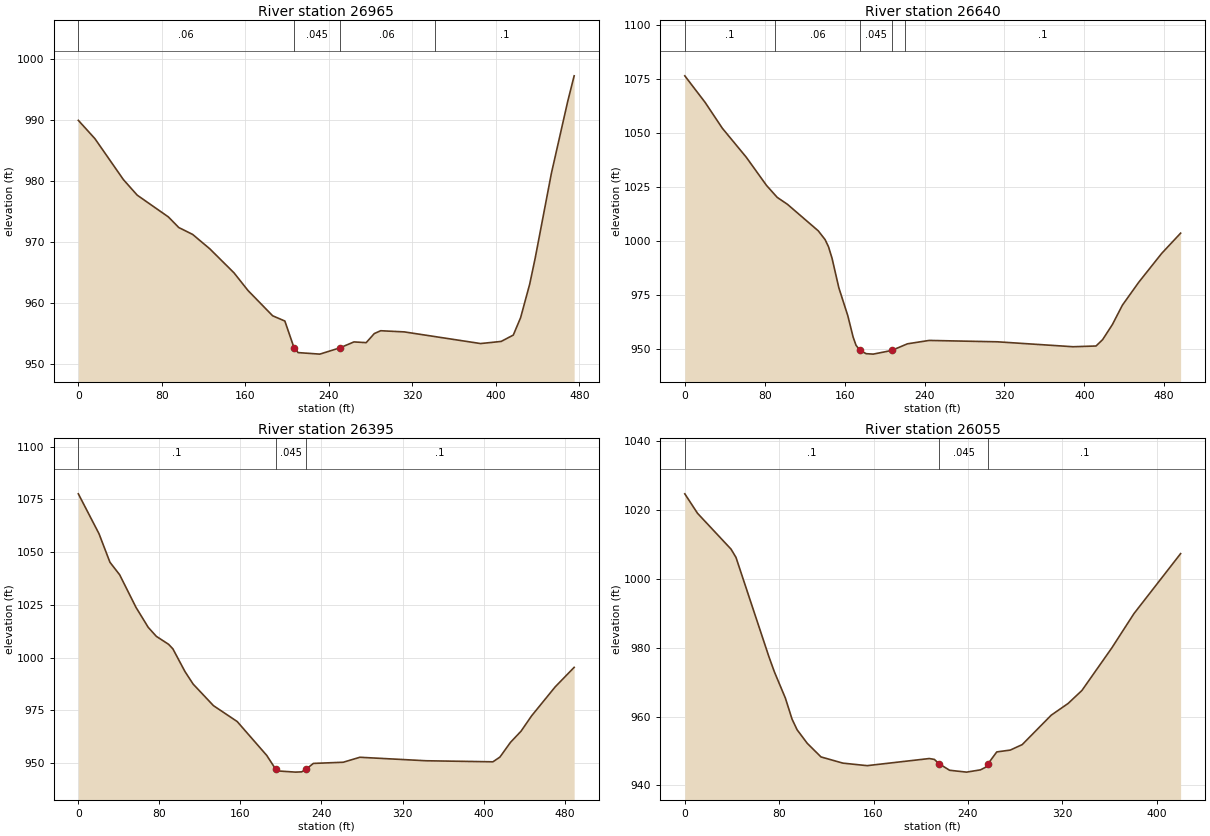
Type RM Length L Ch R = 1 ,26965   ,326.6,324.7,318.1
XS GIS Cut Line= 4
 1668847.3567025 514739.437761781669028.91814266514765.765321345
1669119.66880615 514823.85242128   1669235.10614514966.724538243
#Sta/Elev= 30
       0  989.94    15.9  986.94    43.2  980.23    56.4  977.69    86.3  974.12
    96.2  972.39   109.5  971.26     126  968.89   149.1  964.97   162.5  962.08
   186.1  957.94   197.8  957.08  206.63 952.691   210.5  951.91   231.3  951.66
  250.57952.6916     264  953.66   275.7  953.54   283.5  955.03   289.6  955.49
   312.2   955.3   385.3  953.39     405  953.74   416.6  954.78   423.6  957.62
   432.3  963.11   437.5  967.31   453.1  981.27   468.8  993.09   474.9  997.23
#Mann= 4 ,-1,0
       0     .06       0  206.63    .045       0  250.57     .06       0
  341.21      .1       0
Bank Sta=206.63,250.57
XS Rating Curve= 0 ,0
Exp/Cntr(USF)=0,0
Exp/Cntr=0.3,0.1

Type RM Length L Ch R = 1 ,26640   ,251.2,245,216.9
XS GIS Cut Line= 3
1668699.99628749  514992.83271321668947.95604951515068.978215028
 1669184.6528101515081.957010344
#Sta/Elev= 30
       0 1076.36    20.4 1064.03    37.5 1052.15    61.6 1038.65    81.8 1025.64
    92.5 1020.11   102.8 1016.88   133.6 1004.62   140.5 1000.53   143.9  997.21
   147.4  991.96   154.2   978.3   163.2  965.32   168.5  955.48   171.4  951.67
  175.41949.2401   181.6  947.76   188.6  947.55  207.07  949.24   222.9  952.32
   244.6  953.89   313.1  953.25   388.7  950.97   411.7  951.31   418.3  954.25
   428.1  961.25   438.1   970.2   454.4  980.77   477.4  994.15   496.4 1003.54
#Mann= 5 ,-1,0
       0      .1       0      90     .06       0  175.41    .045       0
  207.07     .06       0     220      .1       0
Bank Sta=175.41,207.07
XS Rating Curve= 0 ,0
Exp/Cntr(USF)=0,0
Exp/Cntr=0.3,0.1

Type RM Length L Ch R = 1 ,26395   ,337.5,339.6,339.2
XS GIS Cut Line= 6
1668819.49654642515420.5360575911668870.23233734515349.125111178
1668913.87824742515288.0399315061668980.69897993515213.361603171
1669036.89473367515162.1235166791669179.12242662515113.130915591
#Sta/Elev= 30
       0 1077.62    20.4 1058.72    31.2 1045.19    40.8 1039.25    56.9 1023.82
      69 1014.33      77 1010.07    89.1 1006.29    93.3 1004.16   105.2  993.43
   113.3  987.45   133.4  977.21   156.8  969.69     186  953.61   194.7947.1705
   198.7  946.22   214.4  945.71   220.5  945.85  225.02947.1721     232  949.84
   261.4  950.39   277.9  952.75   343.1   951.1   409.2   950.6   416.1  952.83
   426.6  959.85     437  965.13   447.4  972.39   470.6  986.08   489.4  995.37
#Mann= 3 ,-1,0
       0      .1       0   194.7    .045       0  225.02      .1       0
Bank Sta=194.7,225.02
XS Rating Curve= 0 ,0
Exp/Cntr(USF)=0,0
Exp/Cntr=0.3,0.1

Type RM Length L Ch R = 1 ,26055   ,253.7,262.9,256.6
XS GIS Cut Line= 2
1669081.84005376515597.5492056871669354.48489279 515277.55021142
#Sta/Elev= 30
       0 1024.72    10.8 1019.06    39.2 1008.65    43.4 1006.25    71.3  977.42
      76  972.96    85.3  965.35    90.9  959.29    95.2  956.18   103.8  952.24
   115.5  948.27   134.1  946.47   154.6  945.74   207.3  947.81   211.6  947.55
   215.6  946.31   224.5   944.4   238.9  943.86   250.7  944.52   254.7  945.21
  257.14 946.294   264.5  949.73     276  950.27   286.1  951.86   310.7  960.41
     325  963.81   336.7  967.58     362  979.92   380.8   989.9   420.4 1007.35
#Mann= 3 ,-1,0
       0      .1       0   215.6    .045       0  257.14      .1       0
Bank Sta=215.6,257.14
XS Rating Curve= 0 ,0
Exp/Cntr(USF)=0,0
Exp/Cntr=0.3,0.1