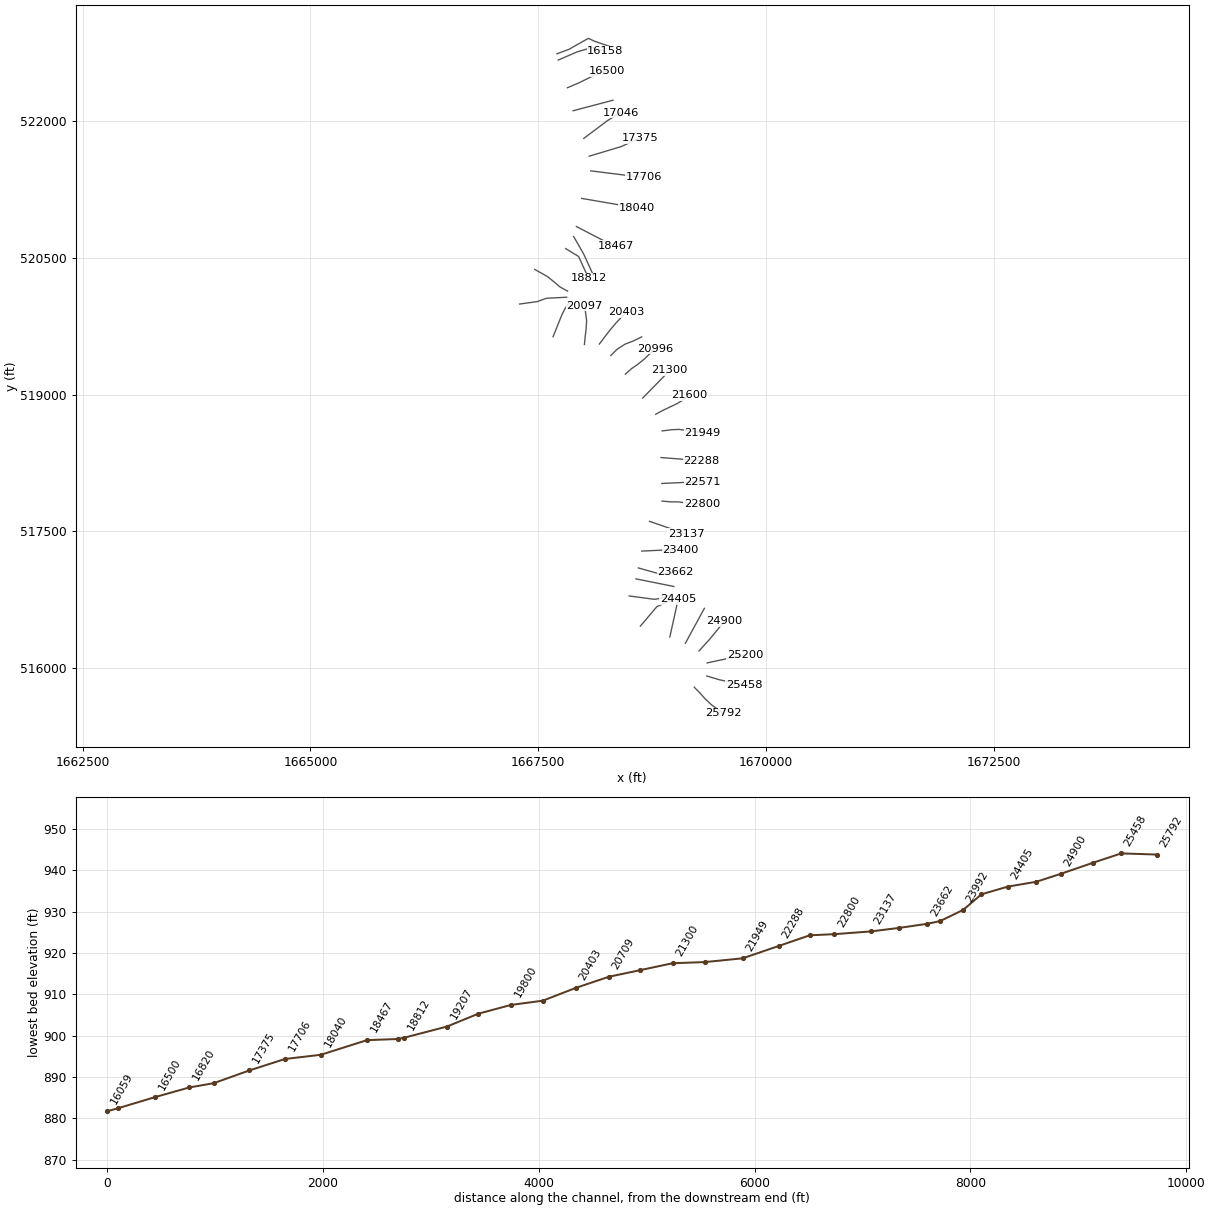
HEC-RAS study WlfRn.prj: WlfRn

--- WlfRn.g01 (geometry) --- (continued)

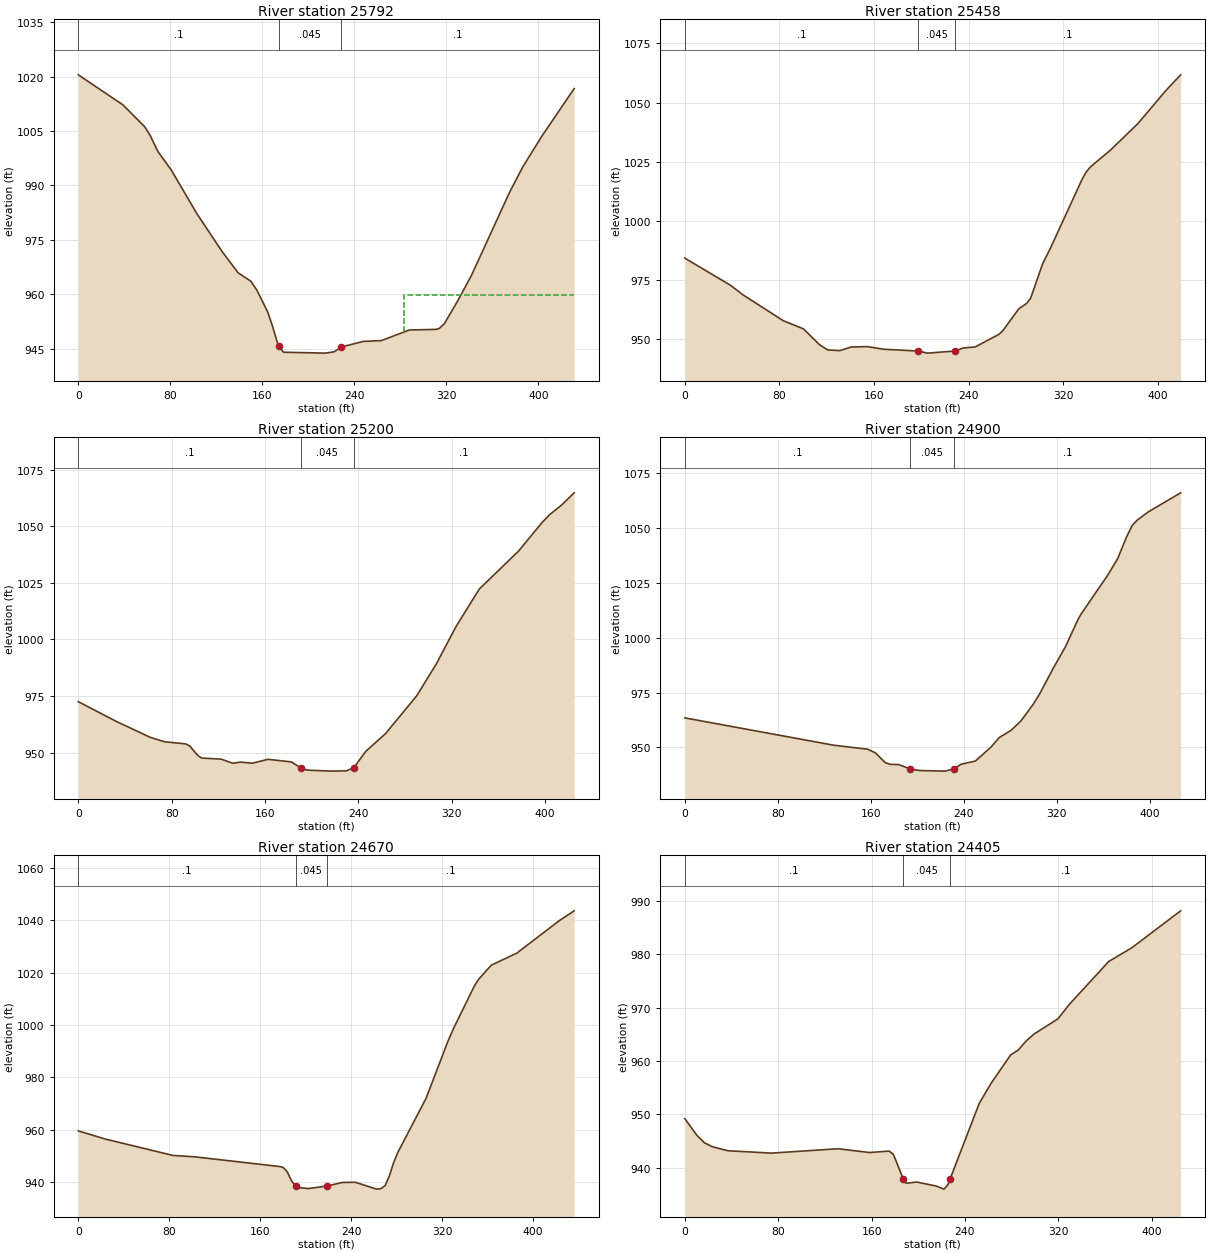
Type RM Length L Ch R = 1 ,25792   ,315.9,334.1,331.1
XS GIS Cut Line= 6
1669213.91537701515786.1258775891669276.25121035515722.605991513
1669327.30721059515664.6169342551669401.20174783515593.612155005
1669462.13371259515549.9488565031669533.22116885515499.010310084
#Sta/Elev= 30
       0 1020.52    38.9 1012.21    57.8 1006.18    62.3  1003.9    69.3  999.34
    80.8  994.29     103  982.28   125.2  971.71     139  965.91     150  963.61
   155.3  961.12   164.6  955.19   168.8  951.28   174.1  945.67   178.5  944.02
   215.1  943.77   222.6  944.15   228.7  945.47   248.1  947.01   263.5  947.22
   287.8  950.15   311.3  950.32     314  950.61   318.4  951.93   330.1  958.27
   341.9  965.22   375.1  988.16   386.5  995.11     403 1003.54   431.2 1016.73
#Mann= 3 ,-1,0
       0      .1       0   174.1    .045       0   228.7      .1       0
#XS Ineff= 2 , 0
                          282.95          959.68
Permanent Ineff=
       F       F
Bank Sta=174.1,228.7
XS Rating Curve= 0 ,0
Exp/Cntr(USF)=0,0
Exp/Cntr=0.3,0.1

Type RM Length L Ch R = 1 ,25458   ,246,258.3,261.3
XS GIS Cut Line= 3
1669351.72415651 515909.19912225 1669489.9039875515867.936344794
 1669758.8061928 515811.19159084
#Sta/Elev= 30
       0  984.23    38.7  972.72    48.9  968.78    83.2  957.77   100.3   954.3
     114  947.54   120.8  945.39   131.1  945.13   140.7  946.65   154.4   946.8
   168.2  945.69  197.41944.9265   205.1  944.05  228.16  944.93   235.3  946.22
   245.4  946.67   265.5  952.01   268.8  953.56   282.3  962.82     289  965.12
   292.3  967.32   302.4  981.85   309.1  988.57   335.9 1017.73   339.3  1020.7
   342.7 1022.77   359.4 1029.76   382.9 1041.12   406.3 1054.96     419 1061.74
#Mann= 3 ,-1,0
       0      .1       0  197.41    .045       0  228.16      .1       0
Bank Sta=197.41,228.16
XS Rating Curve= 0 ,0
Exp/Cntr(USF)=0,0
Exp/Cntr=0.3,0.1

Type RM Length L Ch R = 1 ,25200   ,284.4,300,312.8
XS GIS Cut Line= 6
 1669354.4249385516053.1775088461669440.00055476516071.426160008
1669513.35145792516087.0675329271669611.15244342516107.923134252
1669684.50334659516123.5645071721669770.07929093516141.812830254
#Sta/Elev= 30
       0  972.51    31.8  963.98    61.9  956.69    74.3  954.76    92.1  953.85
    95.5  952.93   102.2  948.85   105.6  947.59   122.3  947.13   132.4   945.3
   139.1   945.8   149.2  945.33   162.6  947.04   182.7  945.88   190.5943.2922
   196.1  942.27   216.3  941.82   229.7  941.94  236.07943.2916   246.4  950.57
   263.2  958.34   290.1  975.14   306.8  989.14   323.6 1005.59   343.7 1022.29
   377.3 1039.05   397.4 1051.63   404.1 1055.22   414.2 1059.39     425 1064.81
#Mann= 3 ,-1,0
       0      .1       0   190.5    .045       0  236.07      .1       0
Bank Sta=190.5,236.07
XS Rating Curve= 0 ,0
Exp/Cntr(USF)=0,0
Exp/Cntr=0.3,0.1

Type RM Length L Ch R = 1 ,24900   ,224.5,229.5,231.5
XS GIS Cut Line= 6
1669266.17708351516184.9472584281669325.68713509516250.773570344
1669376.75527443516305.8918984231669440.32634151516383.084329337
1669488.00472385516440.978898585 1669543.6292845516508.522726759
#Sta/Elev= 30
       0  963.42   128.1  950.95   157.4  949.12   163.9  947.46   172.4  943.01
   176.6  942.23   184.1   942.1  194.06940.0939   202.1   939.4   223.7  939.13
  231.42 940.094   237.7  942.29   249.9  943.72   263.3  950.09   270.5  954.48
   280.8  957.83     289  961.98   299.9  969.82   305.3  974.48   316.9  986.13
   327.3  995.83   338.1 1008.25   340.7 1010.71   363.7 1028.51   372.2 1036.03
   379.9 1045.97   384.9 1051.32   389.2  1053.7   398.5 1057.37   426.4  1066.1
#Mann= 3 ,-1,0
       0      .1       0  194.06    .045       0  231.42      .1       0
Bank Sta=194.06,231.42
XS Rating Curve= 0 ,0
Exp/Cntr(USF)=0,0
Exp/Cntr=0.3,0.1

Type RM Length L Ch R = 1 ,24670   ,250.8,265.2,264.6
XS GIS Cut Line= 2
1669115.96713814516269.0921260651669324.40606332516652.038058379
#Sta/Elev= 30
       0  959.48    23.2  956.41    83.1  950.09   102.5  949.54   177.5  945.81
   180.1  945.47   182.3  944.53   183.9  943.64   187.6  940.23  191.02938.4033
   195.1  937.71   202.5  937.41   218.6  938.39   232.4  939.75   243.6  939.81
   262.3  937.19     266  937.37   269.8  938.55   273.5  942.24   277.2  947.26
     281  951.29   305.7  971.88     325  993.75   329.8  998.56   348.2 1014.87
   351.9 1017.44   363.1 1022.88   385.6  1027.5   422.9 1039.92     436 1043.69
#Mann= 3 ,-1,0
       0      .1       0  191.02    .045       0   218.6      .1       0
Bank Sta=191.02,218.6
XS Rating Curve= 0 ,0
Exp/Cntr(USF)=0,0
Exp/Cntr=0.3,0.1

Type RM Length L Ch R = 1 ,24405   ,261.3,242.6,240.1
XS GIS Cut Line= 2
1668945.53050045516338.4708371961669037.09281901516753.194280062
#Sta/Elev= 30
       0  949.21    10.3   946.1      17  944.66    23.8  943.93    37.2  943.19
    74.2  942.75   131.3  943.57   158.2  942.86     175  943.13   178.3  942.59
   179.4  942.14   187.2937.8577   188.4  937.27   190.4  937.12   198.6  937.34
   215.3  936.59     222  936.01   225.4  936.83  227.15937.8616   252.2  952.06
   262.3   955.8   279.1  961.13   285.8  962.07   292.2   963.7   299.3  965.06
   319.7   967.9   329.5  970.62   363.1  978.61     383   981.2   424.7   988.1
#Mann= 3 ,-1,0
       0      .1       0   187.2    .045       0  227.15      .1       0
Bank Sta=187.2,227.15
XS Rating Curve= 0 ,0
Exp/Cntr(USF)=0,0
Exp/Cntr=0.3,0.1

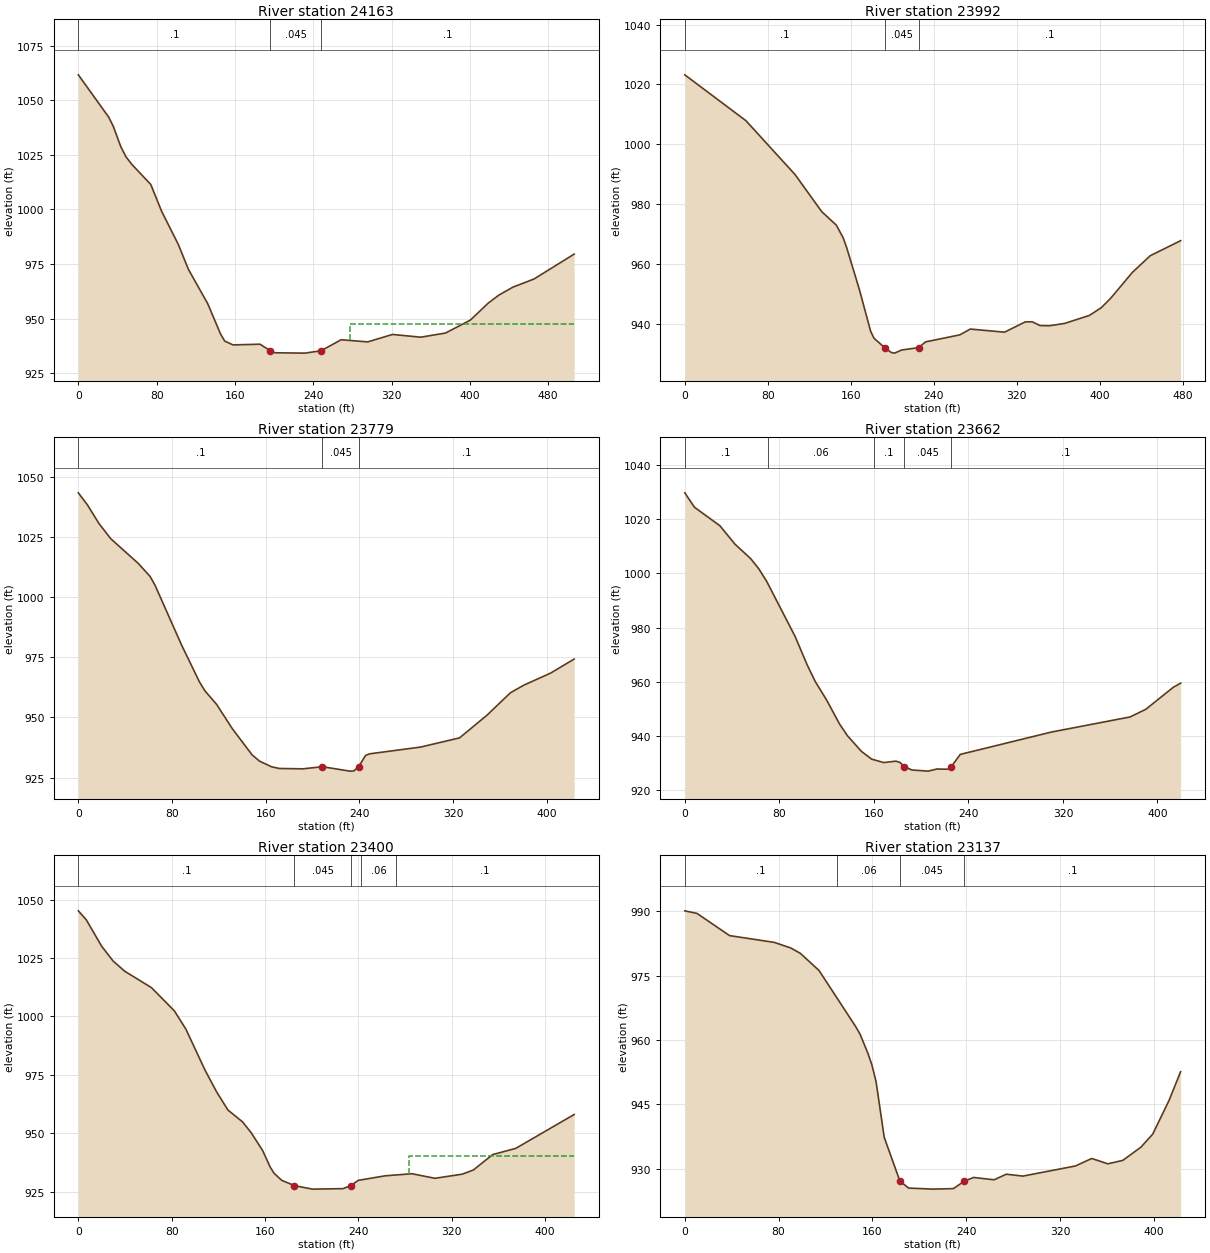
Type RM Length L Ch R = 1 ,24163   ,190.1,170.3,150.7
XS GIS Cut Line= 3
1668622.43064584516457.6021646331668802.84787231 516670.35274696
1669009.22877851516766.231200844
#Sta/Elev= 30
       0 1061.59    31.1 1042.18    35.7 1038.01    43.5 1028.58    48.6 1024.11
    54.9 1020.46      74 1011.39      85  999.19   102.2  983.86   112.5  972.48
   132.3  956.71   145.1   943.1   149.5  939.68   158.1  937.92   185.6  938.25
  196.12 935.228     201  934.32   231.3  934.16  247.87935.2288   268.5  940.29
   295.6   939.3   320.9  942.71   349.8  941.46   375.1  943.36   400.5  949.29
   418.6  957.01   429.4  960.67   443.9  964.36   465.6  968.12   506.5   979.5
#Mann= 3 ,-1,0
       0      .1       0  196.12    .045       0  247.87      .1       0
#XS Ineff= 2 , 0
                          277.26          947.71
Permanent Ineff=
       F       F
Bank Sta=196.12,247.87
XS Rating Curve= 0 ,0
Exp/Cntr(USF)=0,0
Exp/Cntr=0.3,0.1

Type RM Length L Ch R = 1 ,23992   ,204.4,213,202.3
XS GIS Cut Line= 4
1668499.24259916516788.4482390261668776.69877388516751.394824627
1668841.57261775516761.3611318321668966.96803626 516804.10087575
#Sta/Elev= 30
       0 1023.22      59  1007.9   106.3  989.95     132  977.58   146.1  973.07
   152.7  968.83     156  965.64   168.3  951.61   179.2  937.62   182.5  935.31
   192.7932.2067     199   930.6   202.3  930.38     209  931.42  225.36 932.206
   232.1  934.13   265.2  936.48   275.2  938.41   308.3  937.37   328.3  940.82
   334.9  940.83   342.6  939.57   351.7  939.52   366.1  940.28   389.9  942.94
   401.4   945.5   410.7  948.73   431.5  957.32   448.7  962.87     478  967.89
#Mann= 3 ,-1,0
       0      .1       0   192.7    .045       0  225.36      .1       0
Bank Sta=192.7,225.36
XS Rating Curve= 0 ,0
Exp/Cntr(USF)=0,0
Exp/Cntr=0.3,0.1

Type RM Length L Ch R = 1 ,23779   ,114,117.4,111
XS GIS Cut Line= 2
1668574.10451511516975.899671697 1668989.3221252516892.463508913
#Sta/Elev= 30
       0 1043.42     7.7 1038.46    17.8 1030.54    27.8 1024.29    51.2 1014.07
    61.3 1008.65    65.6 1004.91      88  980.32   103.5  964.75   108.1   961.1
   118.2  955.39   131.5  945.36   148.3  934.53   154.7  931.87     165   929.5
   171.7  928.79   191.8  928.64   208.5  929.53   231.9  927.69   235.3  927.77
  239.44929.5063   245.3   934.2   248.7  934.88   292.2  937.68   325.6  941.51
   349.1  950.97   369.1  960.29   380.4  963.41   403.3  968.43   423.5  974.29
#Mann= 3 ,-1,0
       0      .1       0   208.5    .045       0  239.44      .1       0
Bank Sta=208.5,239.44
XS Rating Curve= 0 ,0
Exp/Cntr(USF)=0,0
Exp/Cntr=0.3,0.1

Type RM Length L Ch R = 1 ,23662   ,251.7,262,266.8
XS GIS Cut Line= 3
1668600.04936978517095.826733997 1668847.4285864517026.253534694
1669007.74190484517053.372000592
#Sta/Elev= 30
       0 1029.71     8.2 1024.39    29.7 1017.57    42.3 1010.85    55.9 1005.36
    62.7 1001.63    69.4  996.97    93.4  976.68   103.6  966.21   110.4  960.09
   120.2  953.14   130.9  944.47   137.7  940.07   149.4  934.36   158.1  931.47
   168.4  930.19   178.6  930.72     182  930.27  185.76928.7292   192.2  927.46
   205.9  927.04   213.3  927.82   222.9  927.74  225.58928.7292   233.1  933.21
   310.2  941.45   376.8  947.02   390.1  949.84   413.4  957.97   419.6  959.48
#Mann= 5 ,-1,0
       0      .1       0      70     .06       0     160      .1       0
  185.76    .045       0  225.58      .1       0
Bank Sta=185.76,225.58
XS Rating Curve= 0 ,0
Exp/Cntr(USF)=0,0
Exp/Cntr=0.3,0.1

Type RM Length L Ch R = 1 ,23400   ,272.2,262.7,253.9
XS GIS Cut Line= 6
1668637.19671418517281.108123839 1668724.6056601517285.099913761
 1668799.5244735517288.5844868421668899.41666217517293.229818761
1668974.33580367517296.7130795121669061.87696718517297.442736834
#Sta/Elev= 30
       0 1045.19     6.8 1041.36      20 1030.03    29.8 1023.71    39.7 1019.36
    62.7  1012.3    82.4 1002.31    92.2  994.53   108.6  976.99   118.5  967.71
   128.2  959.92   140.8  954.81   148.1  950.23   157.9  942.63   164.5  935.45
   167.8  932.83   174.3  929.82  185.07927.5737   200.6  926.04   226.9  926.24
  233.63927.5735     240   929.8     263  931.74     286  932.63   305.7  930.67
   329.1  932.45   338.6  934.22   355.1  940.81     375   943.5     425  957.99
#Mann= 5 ,-1,0
       0      .1       0  185.07    .045       0  233.63      .1       0
   242.5     .06       0   272.5      .1       0
#XS Ineff= 2 , 0
                          283.75          940.14
Permanent Ineff=
       F       F
Bank Sta=185.07,233.63
XS Rating Curve= 0 ,0
Exp/Cntr(USF)=0,0
Exp/Cntr=0.3,0.1

Type RM Length L Ch R = 1 ,23137   ,330.1,337,337.1
XS GIS Cut Line= 2
 1668722.7686222517607.6959554261669122.52120285517469.749478832
#Sta/Elev= 30
       0   990.1    10.4   989.5    38.2  984.32    76.3  982.74    90.2  981.46
    98.5   980.2   114.5  976.18   145.8  963.08   149.5  961.33   156.2  956.86
   159.6  954.15   163.1  950.34   170.1  937.27  183.46927.0683   190.9  925.44
   211.7  925.19   229.1  925.31  238.51927.0654   246.4  927.91   263.8  927.37
   274.2  928.67   288.4  928.23   333.2  930.59   347.1  932.34   360.9  931.09
   373.6   931.9   389.1  934.99   399.1  938.02     413  945.86   422.9  952.58
#Mann= 4 ,-1,0
       0      .1       0     130     .06       0  183.46    .045       0
  238.51      .1       0
Bank Sta=183.46,238.51
XS Rating Curve= 0 ,0
Exp/Cntr(USF)=0,0
Exp/Cntr=0.3,0.1

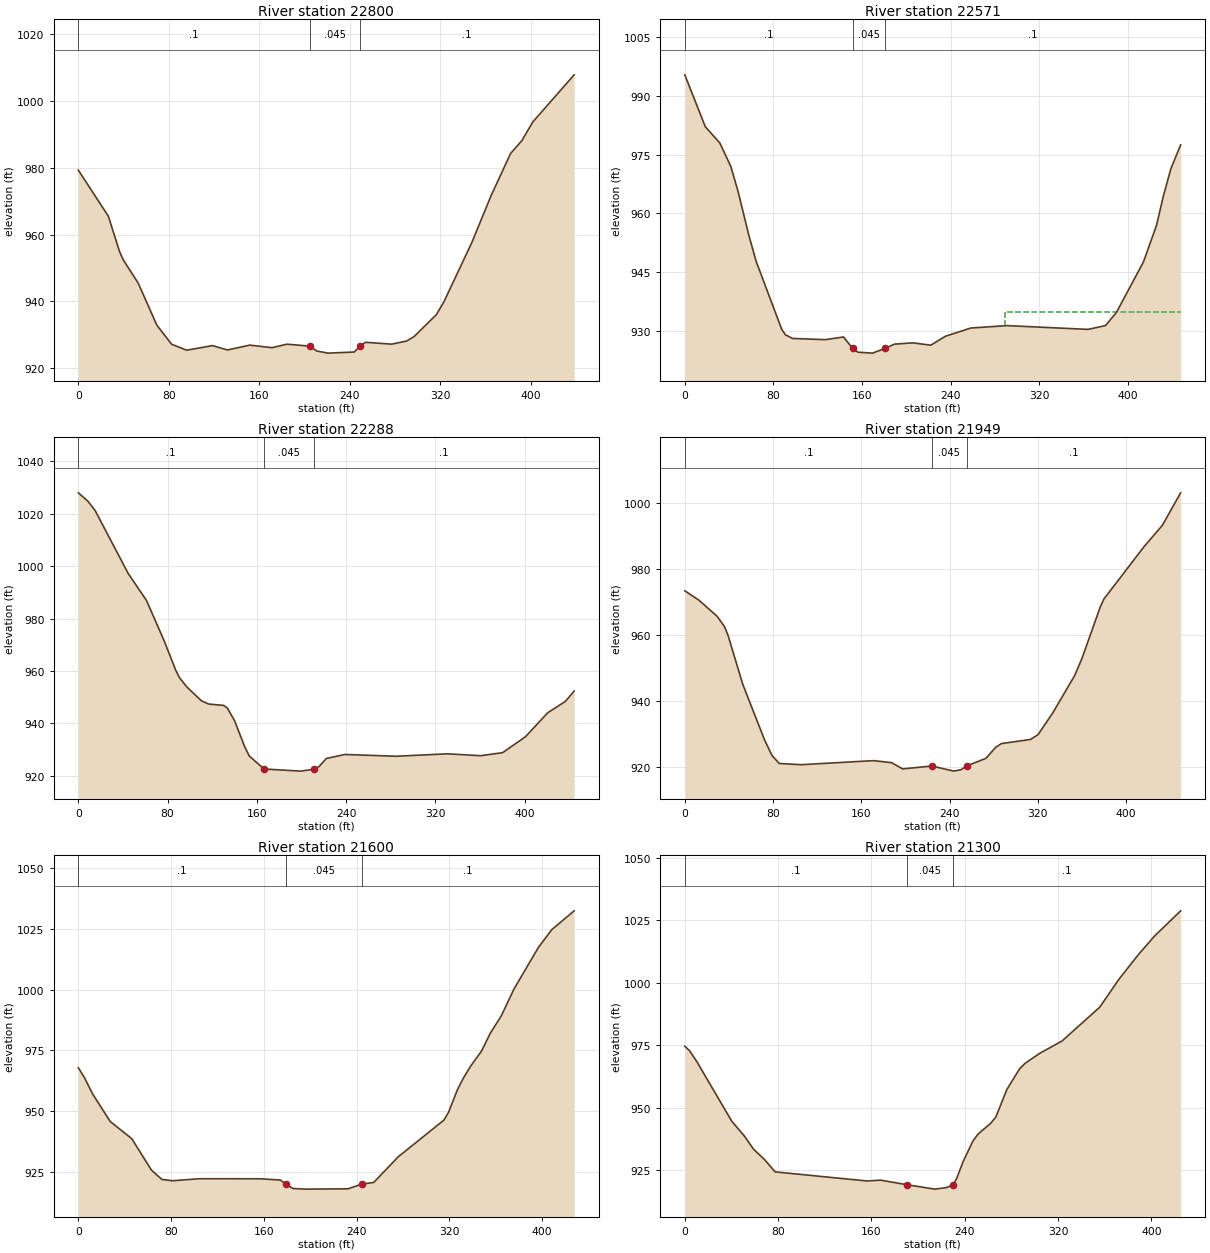
Type RM Length L Ch R = 1 ,22800   ,223,229.4,235.4
XS GIS Cut Line= 6
1668860.39672709517830.255975679 1668957.7446295517821.218920261
1669035.61619292517821.6165572551669134.84499709517809.211070254
1669209.66046426 517803.285885261669297.19408184517799.688779593
#Sta/Elev= 30
       0  979.35    26.5  965.58    36.4     955    39.7  952.49    52.9  945.52
    69.4  932.91    82.5  927.19    95.7  925.41   118.7  926.78   131.8  925.47
   151.5  926.93   171.2  926.16   184.4  927.21   204.5  926.63   210.8  925.17
   220.7  924.53   243.9  924.86  249.21926.6453   253.8  927.78   276.9  927.22
   290.1  928.15   296.7  929.46   316.4  936.02     323  939.79   347.8  957.63
     365  971.81   382.1  984.34     392  988.17   401.9  993.86   438.3 1007.91
#Mann= 3 ,-1,0
       0      .1       0   204.5    .045       0  249.21      .1       0
Bank Sta=204.5,249.21
XS Rating Curve= 0 ,0
Exp/Cntr(USF)=0,0
Exp/Cntr=0.3,0.1

Type RM Length L Ch R = 1 ,22571   ,276.7,283,270.5
XS GIS Cut Line= 2
1668858.47675395 518023.557458581669305.70026827 518044.47768886
#Sta/Elev= 30
       0  995.38    18.5  982.13    31.6  977.97    41.5  972.02    48.1  965.57
    57.9  954.29    64.5  947.65    87.5  930.35    90.8  928.96    97.3     928
   126.9  927.69   143.3  928.38  151.58925.4608   156.4  924.48   169.6  924.25
  180.69 925.462   189.3  926.54   205.7  926.88   222.1  926.28   235.3  928.56
   258.3  930.67   291.1  931.28   364.2  930.32   379.8  931.29   389.6  934.58
   414.1  947.54   425.8  956.79   432.3  964.58   438.9  971.38   447.7  977.47
#Mann= 3 ,-1,0
       0      .1       0  151.58    .045       0  180.69      .1       0
#XS Ineff= 2 , 0
                          289.17          934.64
Permanent Ineff=
       F       F
Bank Sta=151.58,180.69
XS Rating Curve= 0 ,0
Exp/Cntr(USF)=0,0
Exp/Cntr=0.3,0.1

Type RM Length L Ch R = 1 ,22288   ,335.3,338.6,331.7
XS GIS Cut Line= 2
1668848.88712263518308.2348744921669291.95670262518273.510623949
#Sta/Elev= 30
       0 1028.01     8.4  1024.9      15 1021.29    44.6  997.27    61.1   986.9
    77.5  970.91    87.4  960.13    90.7  957.38    97.3  953.84   110.4  948.55
     117  947.32   130.2  946.82   133.5  945.83     140     941   149.1  931.03
   153.2   927.5   166.4  922.52   199.3  921.71   211.5  922.46   215.7  923.43
   222.3  926.54   238.8  928.07   284.8  927.39   330.9  928.32   360.5   927.6
   380.3  928.77   400.8  934.86   420.7     944   436.5  948.33   444.4  952.27
#Mann= 3 ,-1,0
       0      .1       0   166.4    .045       0   211.5      .1       0
Bank Sta=166.4,211.5
XS Rating Curve= 0 ,0
Exp/Cntr(USF)=0,0
Exp/Cntr=0.3,0.1

Type RM Length L Ch R = 1 ,21949   ,330.8,349.3,348.6
XS GIS Cut Line= 6
1668860.96899787   518600.4100871668962.72371562518613.385782834
1669046.99585678518617.5448952431669145.91757495518602.901879918
1669220.10935571518591.9189622511669306.66594113518579.105995741
#Sta/Elev= 30
       0  973.38    12.8  970.54    29.3  965.65      36  962.51    39.3  959.78
    52.5  945.06    72.3  928.17      79  923.46    85.6  921.01   105.4  920.64
   171.1  921.87   187.5  921.26   197.5  919.37     224  920.24   243.9  918.69
   250.5  919.13   255.4  920.23     273  922.57   281.6  925.85     287  927.04
   313.4   928.3   320.2  929.74   333.5   936.3   353.4  947.64     360  952.82
   376.6  968.43   379.9  970.87   416.4  986.79   432.9  993.21   449.5 1003.09
#Mann= 3 ,-1,0
       0      .1       0     224    .045       0   255.4      .1       0
Bank Sta=224,255.4
XS Rating Curve= 0 ,0
Exp/Cntr(USF)=0,0
Exp/Cntr=0.3,0.1

Type RM Length L Ch R = 1 ,21600   ,288.9,300,308.8
XS GIS Cut Line= 6
1668790.39128967518784.0168634211668867.63588583518825.324851677
1668935.33916251518857.606939346 1669025.6185095518900.614071175
1669089.78832868518940.2796742621669160.25603551518995.535469249
#Sta/Elev= 30
       0   967.8       5  963.99    12.2  957.13    27.5  945.66    46.1  938.57
    63.1  925.58    72.1  921.77    81.1  921.23   104.6  922.07   156.7  922.05
   174.3  921.53   178.9919.8134   185.2  918.03   195.7  917.78   232.6  917.91
  244.23919.8137   254.8  920.55   275.8  931.07   315.4  946.29   319.3  949.48
     327  958.84     332  963.49   338.2   968.4   347.8  974.76   355.3  982.07
   364.8  989.26   375.8 1000.36   396.9 1017.53   408.5 1024.85   427.6 1032.52
#Mann= 3 ,-1,0
       0      .1       0   178.9    .045       0  244.23      .1       0
Bank Sta=178.9,244.23
XS Rating Curve= 0 ,0
Exp/Cntr(USF)=0,0
Exp/Cntr=0.3,0.1

Type RM Length L Ch R = 1 ,21300   ,305.5,303.8,299.7
XS GIS Cut Line= 6
1668647.71572201518961.7045001691668708.94558643519024.211593002
  1668761.428093519077.7892417611668831.40564334519149.225778669
1668883.88880609519202.8030993341668945.11867051519265.309864089
#Sta/Elev= 30
       0  974.63     4.1  972.85    10.2  968.58    40.3  944.63      51  938.79
    58.9  933.49    68.2   929.4    77.4   924.4   156.3  920.75   167.9  921.09
  190.38919.2589   214.3   917.5   224.5  918.13  229.79919.2604   232.9  921.61
   238.5  928.44   246.8  936.59   251.4  939.54     262  943.74   266.6  946.31
     276  957.28     287  965.63   291.6  967.78   304.2   971.8   323.4  976.75
   355.7  990.27   372.1 1001.42   388.5  1011.1   402.2 1018.49     425 1028.79
#Mann= 3 ,-1,0
       0      .1       0  190.38    .045       0  229.79      .1       0
Bank Sta=190.38,229.79
XS Rating Curve= 0 ,0
Exp/Cntr(USF)=0,0
Exp/Cntr=0.3,0.1

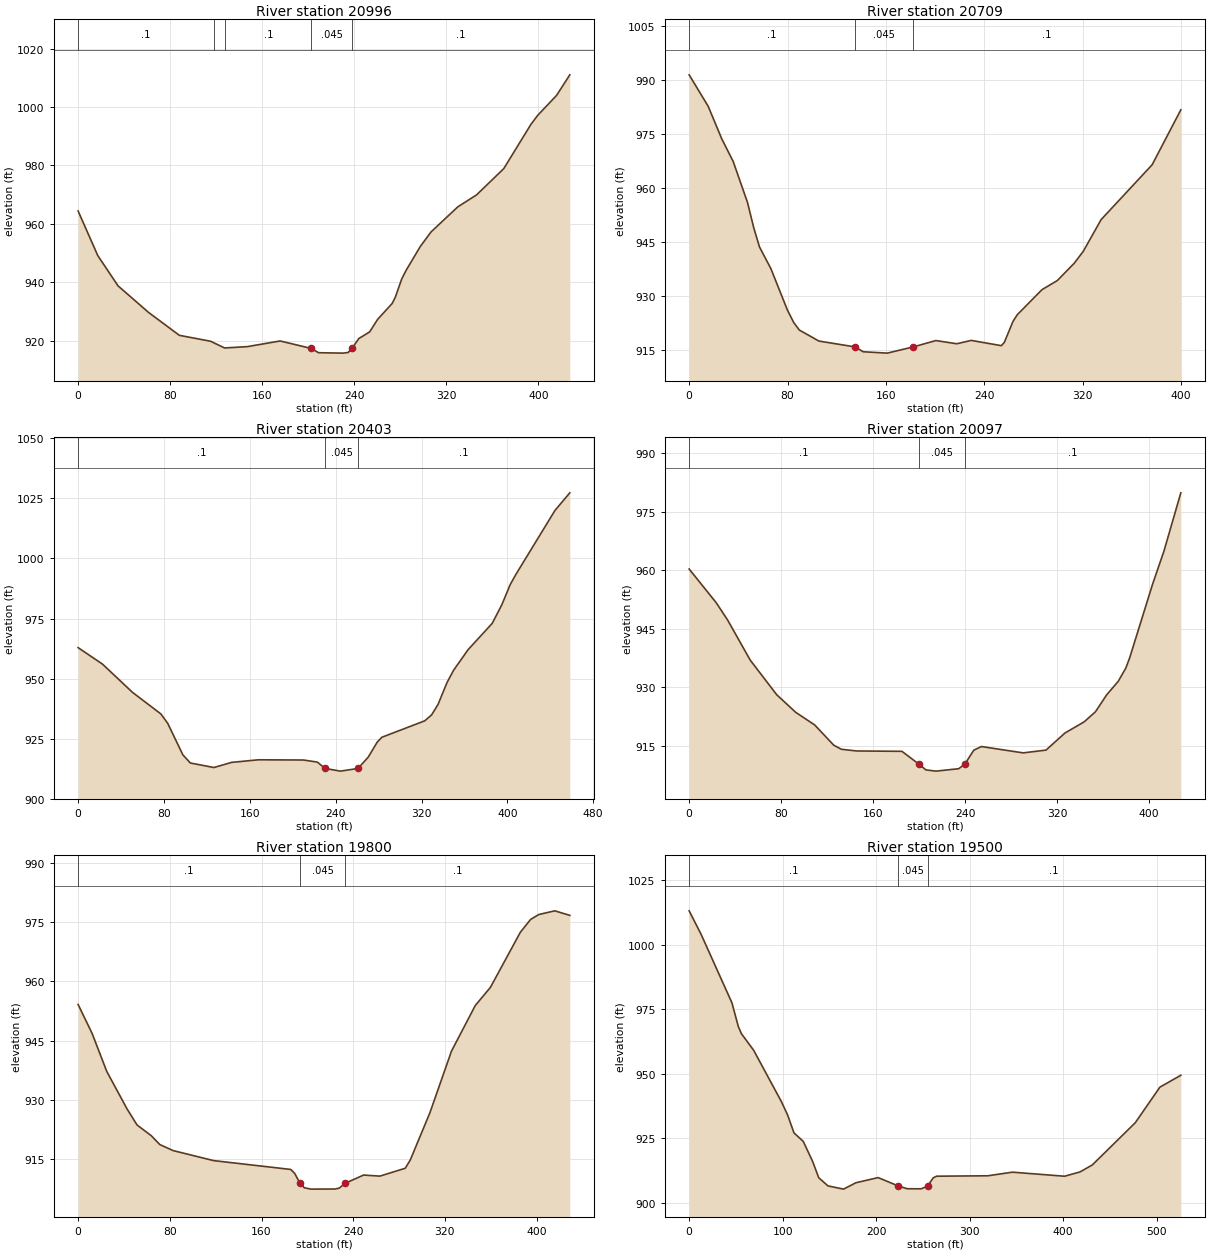
Type RM Length L Ch R = 1 ,20996   ,288.9,287.2,276.7
XS GIS Cut Line= 6
1668457.42935717519224.2384239291668523.01157509519282.957466587
1668585.00554559519325.1680120831668663.30033651519387.717099592
1668717.54989992519440.7324135011668781.45626818519501.680454344
#Sta/Elev= 30
       0  964.42    17.1  949.17    34.7  938.82    61.2  929.74      88   921.9
   115.1  919.88   127.3  917.58   147.1  918.03   175.6  919.97  202.72917.4055
     209  915.95   230.2  915.81   234.7  916.03  238.03917.4079     244   920.8
   253.4  923.06   260.4  927.38     273   932.8   275.7  934.91   281.3  941.18
   285.1  944.11   297.5  952.32   306.8  957.27     330  965.83   346.3  969.92
     370  978.92   393.7  994.11   399.6  997.19   415.9 1003.96   427.4    1011
#Mann= 5 ,-1,0
       0      .1       0  118.03     .06       0  128.03      .1       0
  202.72    .045       0  238.03      .1       0
Bank Sta=202.72,238.03
XS Rating Curve= 0 ,0
Exp/Cntr(USF)=0,0
Exp/Cntr=0.3,0.1

Type RM Length L Ch R = 1 ,20709   ,293.3,306.5,292.7
XS GIS Cut Line= 5
1668298.36645371519429.0330892171668368.46628051519498.848767087
1668454.55403484 519553.510731251668542.38555209519587.324968085
1668636.69474667  519632.9485645
#Sta/Elev= 30
       0  991.51    15.5  982.76    26.5  973.75    35.8  967.46    47.4  956.12
    52.6  948.96    57.2  943.71    66.5  937.67    79.8  926.28      85  922.74
    89.6  920.64   105.5  917.58  134.73915.9697   141.6  914.61   161.1  914.23
  182.42915.9693   200.6  917.72   217.6  916.83   229.4  917.76   253.9   916.3
   256.3  917.23   263.3  923.01   266.8  924.89   286.9  931.85   299.4  934.39
   313.2  939.22   320.5  942.52     335  951.31   376.5  966.55   399.8  981.79
#Mann= 3 ,-1,0
       0      .1       0  134.73    .045       0  182.42      .1       0
Bank Sta=134.73,182.42
XS Rating Curve= 0 ,0
Exp/Cntr(USF)=0,0
Exp/Cntr=0.3,0.1

Type RM Length L Ch R = 1 ,20403   ,294.5,305.7,313.1
XS GIS Cut Line= 6
1668171.89679176 519554.740059511668240.13582851519645.094865665
1668290.39491434519709.9293816691668355.34294717519786.714661166
1668406.58529876519841.4261659231668466.36765951519905.255434588
#Sta/Elev= 30
       0  962.88    22.6  956.08    50.7  944.29    77.1  935.33    83.5  931.41
    97.6  918.32   104.6  914.92   126.5  913.04   143.1  915.18     168  916.25
     210  916.16   222.9   915.3  230.21912.6468   244.4  911.54  260.81912.6486
   270.4  917.38   278.8  923.65   283.1  925.63     323  932.45   329.4  934.92
   335.4  939.27   343.8  948.38   349.9  953.48   363.4  962.04   385.9  972.98
   394.9  980.76   402.7  989.15   408.4  993.66   444.4 1019.95   458.2 1027.26
#Mann= 3 ,-1,0
       0      .1       0  230.21    .045       0  260.81      .1       0
Bank Sta=230.21,260.81
XS Rating Curve= 0 ,0
Exp/Cntr(USF)=0,0
Exp/Cntr=0.3,0.1

Type RM Length L Ch R = 1 ,20097   ,301.5,296.8,288.8
XS GIS Cut Line= 6
1668008.31312943519550.1865909251668016.51357234519637.352427095
1668025.61263551519711.8001128441668032.03388251519811.754965425
1668022.19860034519887.3181345021668009.71666992519975.244139761
#Sta/Elev= 30
       0  960.29    23.5  951.66    33.4  947.24    53.2  936.89    76.2  928.04
    92.7  923.53   109.2   920.3   125.8   915.1   132.4  914.06   145.6  913.62
   185.1  913.53  199.84910.2479     206  908.76   214.7  908.45   234.5  909.07
  239.84910.2482   247.6  913.82   254.2  914.76   290.5  913.13   310.4  913.84
   326.9  918.22   343.5  921.07   353.4  923.66   363.3  928.06   373.3   931.5
   379.9  934.91   383.2  937.51   403.1  956.37     413  964.87   427.7  979.83
#Mann= 3 ,-1,0
       0      .1       0  199.84    .045       0  239.84      .1       0
Bank Sta=199.84,239.84
XS Rating Curve= 0 ,0
Exp/Cntr(USF)=0,0
Exp/Cntr=0.3,0.1

Type RM Length L Ch R = 1 ,19800   ,313.3,300,284.3
XS GIS Cut Line= 6
1667663.54643051519634.4816979171667696.23763809519715.645249501
1667724.25857942519785.2143360821667761.61972517519877.972680762
1667795.64491959519945.1231370121667850.22223826520018.237164006
#Sta/Elev= 30
       0  954.12    12.2   946.8      25  937.18    42.6  927.75    51.4  923.64
    63.8  920.93    71.3  918.68    82.9  917.16   118.3  914.62   185.5  912.39
     189  911.38  193.58908.8805   197.4  907.75   203.2  907.41   224.4  907.44
   227.9  907.68  232.91908.8821   249.1  910.97   263.3   910.7   285.4  912.69
   289.8  914.77   306.9   926.7   325.8  942.34   346.5  953.84   359.7  958.43
   385.9  972.41   394.8  975.63   401.9  976.87   415.9  977.81     429  976.66
#Mann= 3 ,-1,0
       0      .1       0  193.58    .045       0  232.91      .1       0
Bank Sta=193.58,232.91
XS Rating Curve= 0 ,0
Exp/Cntr(USF)=0,0
Exp/Cntr=0.3,0.1

Type RM Length L Ch R = 1 ,19500   ,307.9,293.3,277
XS GIS Cut Line= 4
1667296.14127578519993.9084291361667490.03817512 520020.65006894
1667591.44161433520057.2218011151667813.41742941520068.586706696
#Sta/Elev= 30
       0 1013.17    12.7 1004.13    45.8  977.48    52.5  968.41    55.8   965.6
      69  959.11    98.8  939.13   105.4  933.95   112.1   927.1     122  923.83
   131.9  916.17   138.6  909.71   148.5  906.56   165.1  905.31   178.3  907.78
   202.1  909.78  223.82906.5065   233.2  905.46   248.2  905.43  254.98906.4855
     261  909.68   264.6  910.32   319.4  910.48   345.7  911.88   401.5  910.31
     418  911.98   431.1  914.67   477.1  931.05   503.4  944.83   525.8  949.44
#Mann= 3 ,-1,0
       0      .1       0  223.82    .045       0  254.98      .1       0
Bank Sta=223.82,254.98
XS Rating Curve= 0 ,0
Exp/Cntr(USF)=0,0
Exp/Cntr=0.3,0.1

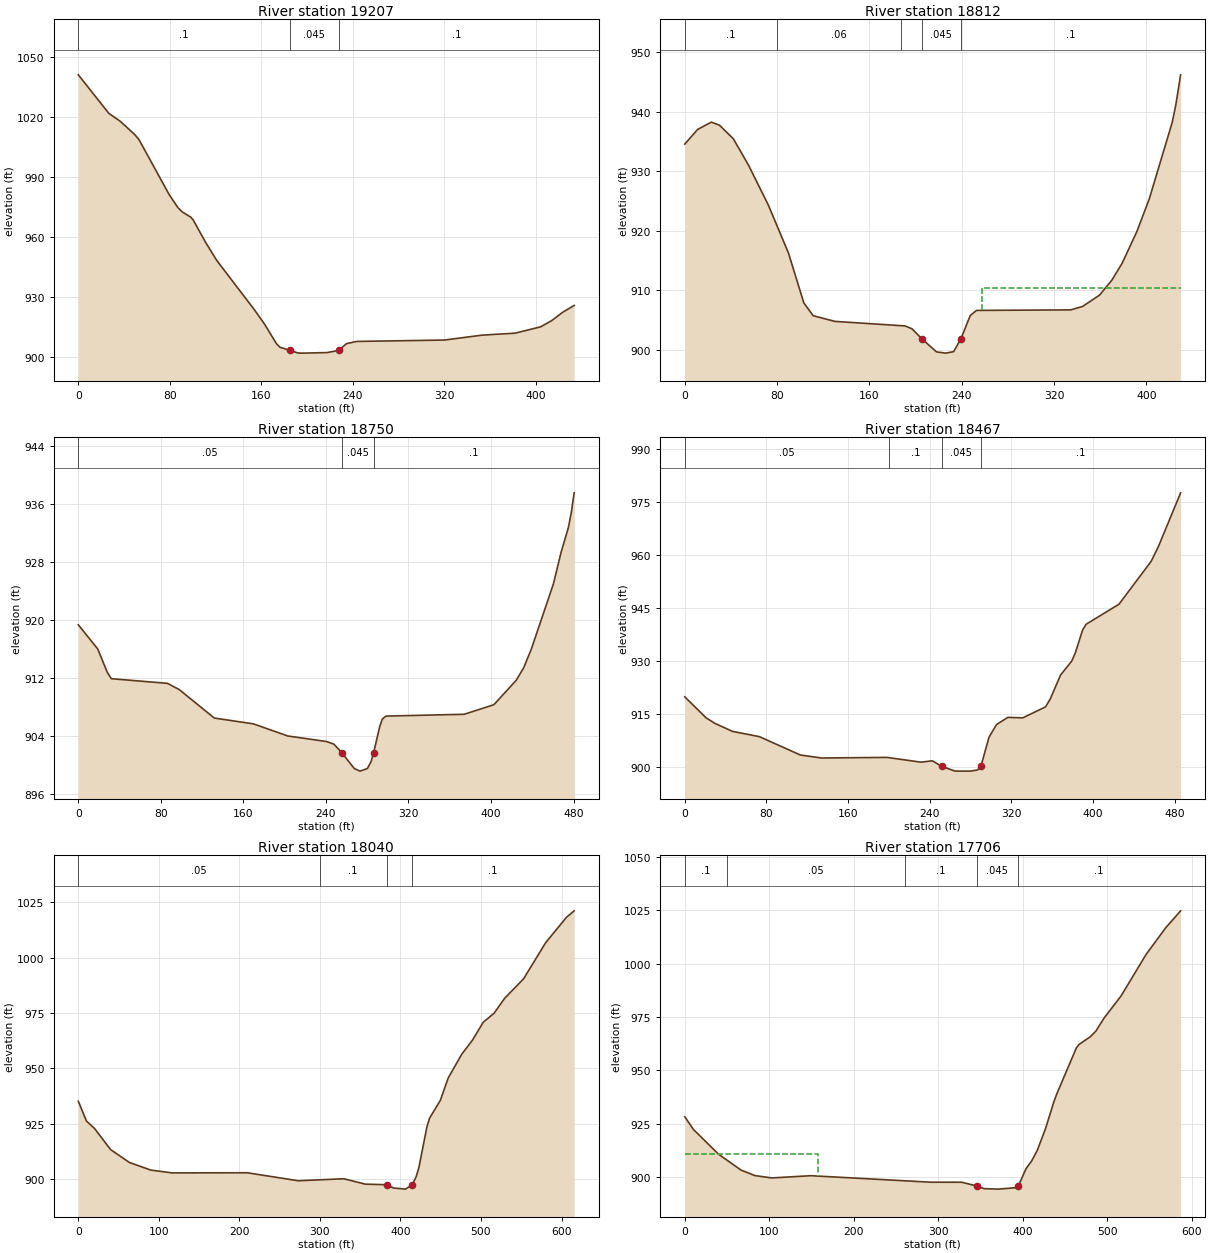
Type RM Length L Ch R = 1 ,19207   ,401.8,394.6,384.7
XS GIS Cut Line= 6
1667462.59866968520374.1997066741667539.44103567 520330.95668292
1667605.48257026 520293.251705841667683.26948817520229.624208421
1667740.41799593520180.8454345911667822.60844834520136.098476842
#Sta/Elev= 30
       0 1041.24    26.7 1021.96    36.5  1018.1    49.3 1011.41    53.1 1008.79
    79.4   981.4      87  974.93    90.7  972.79    98.3  970.12   100.4  968.74
   111.1  957.68     121   948.5   153.4  924.22   162.5  916.92   173.3  906.79
   176.4  905.08   185.1903.5472     192  902.25   196.2  902.18   217.4  902.45
   227.5903.5446   234.4  906.91   243.3  908.02   320.1  908.72   352.6  911.15
   381.7  912.15     404   915.3   413.7  918.39   423.3  922.58   433.4  925.99
#Mann= 3 ,-1,0
       0      .1       0   185.1    .045       0   227.5      .1       0
Bank Sta=185.1,227.5
XS Rating Curve= 0 ,0
Exp/Cntr(USF)=0,0
Exp/Cntr=0.3,0.1

Type RM Length L Ch R = 1 ,18812   ,62.2,62.3,62.5
XS GIS Cut Line= 5
1667801.40860197520603.0934921511667944.08607921520515.888270201
1667985.65030053520424.9356962011668016.82412271520356.721265705
1668053.19281638520277.137435378
#Sta/Elev= 30
       0  934.54    11.1  936.99      23  938.22    30.1   937.7    42.1  935.42
    55.4  930.94    72.4  924.32    89.8   916.3   103.2   907.9   111.3  905.77
   130.1  904.82   190.9  904.06   196.9  903.58  205.33901.9218   218.1  899.71
   226.2   899.5     233  899.75  239.32901.9213   247.4   905.8   252.8  906.66
   334.5  906.75   344.8  907.33   359.4  909.22     370   911.7     379  914.56
   391.7  919.84   402.5  925.33   422.5  938.23   425.5  941.07   429.7  946.15
#Mann= 5 ,-1,0
       0      .1       0      80     .06       0  187.22      .1       0
  205.33    .045       0  239.32      .1       0
#XS Ineff= 2 , 0
                          257.76          910.45
Permanent Ineff=
       F       F
Bank Sta=205.33,239.32
XS Rating Curve= 0 ,0
Exp/Cntr(USF)=0,0
Exp/Cntr=0.3,0.1

Type RM Length L Ch R = 1 ,18750   ,268.2,283,289.6
XS GIS Cut Line= 5
1667889.90089166520734.4342385791667998.64645086 520545.43326247
1668040.21067218 520454.480688471668071.38449436520386.266257974
1668107.75318802520306.682427648
#Sta/Elev= 30
       0  919.33    18.8  916.01    28.1  912.78      32  911.91    86.4  911.27
    97.8  910.41   131.8  906.49   169.7  905.69     203  904.02   240.5  903.26
   247.7   902.9  255.33901.7374   267.4  899.55     273  899.18   280.2  899.54
   283.8   900.5  286.27901.7364   292.2  905.35   294.6  906.34   298.2  906.76
     374  907.01   402.8  908.33   424.5   911.7   431.7  913.43   438.9  915.91
   460.5  924.97   467.9   929.3     475  932.72   477.9  934.85   480.6  937.51
#Mann= 3 ,-1,0
       0     .05       0  255.33    .045       0  286.27      .1       0
Bank Sta=255.33,286.27
XS Rating Curve= 0 ,0
Exp/Cntr(USF)=0,0
Exp/Cntr=0.3,0.1

Type RM Length L Ch R = 1 ,18467   ,421,427.3,430.4
XS GIS Cut Line= 3
1667920.14930692520844.680860079 1668252.5633827520672.389481843
1668355.91130119520630.716893702
#Sta/Elev= 30
       0   919.9    20.8  913.99    29.4  912.42    46.7  910.15    73.2  908.64
   113.2  903.47     134  902.62   198.2  902.79   231.4  901.44   242.6  901.83
  251.65900.2607   264.7  898.92   279.5  898.91   286.9  899.23  290.14  900.26
     298  908.45   305.4  912.07   316.5   914.1   331.2  913.97   353.4  917.06
     358  919.26   368.2  926.08   379.1     930   382.6   932.3   389.7  938.74
   393.2  940.41   425.4  946.07   456.9  958.18     464  962.34   485.8  977.55
#Mann= 4 ,-1,0
       0     .05       0     200      .1       0  251.65    .045       0
  290.14      .1       0
Bank Sta=251.65,290.14
XS Rating Curve= 0 ,0
Exp/Cntr(USF)=0,0
Exp/Cntr=0.3,0.1

Type RM Length L Ch R = 1 ,18040   ,331.3,333.6,334.7
XS GIS Cut Line= 2
 1667977.8812349521153.7382206291668584.67038478521049.560183512
#Sta/Elev= 30
       0  935.07    10.1  926.13    20.1  922.79    40.1  913.22    63.4  907.42
      90  903.97   116.6   902.7   209.9  902.76   273.1  899.15   329.7  900.06
   356.3  897.62  382.71897.3598   391.4  895.88   406.3  895.37  414.69897.3623
   419.6  901.06   422.9  905.11   432.9  923.56   436.2  927.44   449.5  935.45
   459.3  945.57   476.2  956.37   489.5  962.71   502.8  970.76   516.2  974.79
   529.4  981.59   552.7  990.28   580.3 1006.68     606 1018.11   615.7 1021.09
#Mann= 4 ,-1,0
       0     .05       0     300      .1       0  382.71    .045       0
  414.69      .1       0
Bank Sta=382.71,414.69
XS Rating Curve= 0 ,0
Exp/Cntr(USF)=0,0
Exp/Cntr=0.3,0.1

Type RM Length L Ch R = 1 ,17706   ,321.3,331.1,339.1
XS GIS Cut Line= 2
1668076.15836461521456.4140788171668658.12744659521383.631086752
#Sta/Elev= 30
       0  928.25    10.2   922.3      40  910.69    66.4   903.3    82.9   900.7
   102.8  899.59   149.1  900.64   291.2  897.59   327.6  897.58  345.15895.8434
   354.1  894.58   370.6  894.35   390.4  894.98   393.6895.8424   397.1  898.08
   403.7     904   410.3  907.54   416.9  912.48   426.8   922.8   436.7  935.43
     440  938.92   463.2   960.5   466.5  962.17   479.7  965.71   486.3  968.39
   496.2   974.6   516.1  984.86   545.8 1004.34     569 1016.82   586.5 1024.69
#Mann= 5 ,-1,0
       0      .1       0      50     .05       0     260      .1       0
  345.15    .045       0   393.6      .1       0
#XS Ineff= 2 , 0
          157.26  910.84
Permanent Ineff=
       F       F
Bank Sta=345.15,393.6
XS Rating Curve= 0 ,0
Exp/Cntr(USF)=0,0
Exp/Cntr=0.3,0.1

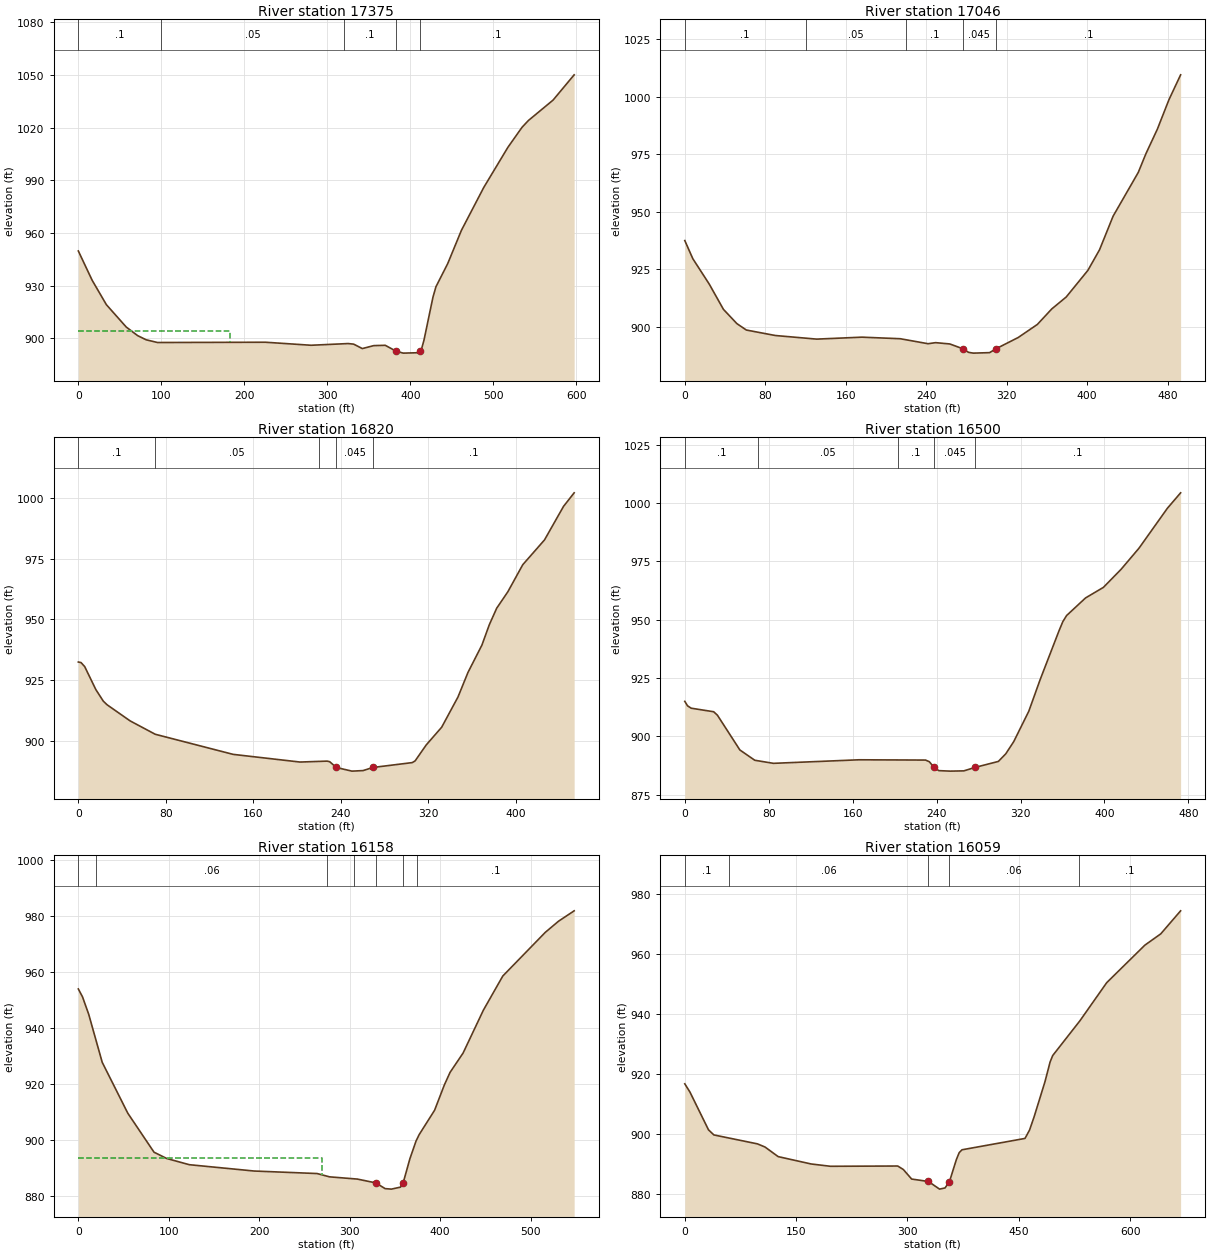
Type RM Length L Ch R = 1 ,17375   ,324.5,328.7,331
XS GIS Cut Line= 3
1668060.51324127521617.3063771411668410.97660853521722.682436755
1668621.96450682 521817.55255829
#Sta/Elev= 30
       0  949.77    16.6  933.13    33.8  919.17    57.7  906.44    71.4  901.55
    81.7  899.17    95.4  897.62   225.6  897.77   280.4  896.05     325  897.02
   331.7  896.69   342.1  894.16   355.8  895.84   369.7  896.03  382.58 892.736
   391.3  891.57   408.1  891.78  411.99892.7341   413.5  893.99   416.4  898.98
   427.2  923.43   430.8  929.38     445  942.59   461.5  961.54   488.4  985.96
   517.5 1008.84   534.6 1020.29   542.3 1024.15   571.9 1035.73   597.3 1050.13
#Mann= 5 ,-1,0
       0      .1       0     100     .05       0     320      .1       0
  382.58    .045       0  411.99      .1       0
#XS Ineff= 2 , 0
          183.25  904.13
Permanent Ineff=
       F       F
Bank Sta=382.58,411.99
XS Rating Curve= 0 ,0
Exp/Cntr(USF)=0,0
Exp/Cntr=0.3,0.1

Type RM Length L Ch R = 1 ,17046   ,232.8,226.3,220
XS GIS Cut Line= 3
1668001.27109399521812.7715189771668262.65163693 522009.20367248
1668404.56098283522095.202169477
#Sta/Elev= 30
       0  937.44       8  929.54    24.3  918.52    38.4  907.54    51.8  901.32
    61.2  898.54      90  896.16     131  894.59   176.1  895.44   214.2  894.76
   241.8  892.59   249.3  893.05   263.4  892.49  276.26890.4318   282.1  888.84
   286.8   888.5     303  888.71  309.51890.4302   331.4  895.28   350.5  900.98
   364.8  907.71   379.2  912.92   400.7  924.48   412.3  933.44   425.8  948.06
   450.8  967.07   458.3  975.11   469.8   985.9   481.3  998.69   492.9  1009.5
#Mann= 5 ,-1,0
       0      .1       0     120     .05       0     220      .1       0
  276.26    .045       0  309.51      .1       0
Bank Sta=276.26,309.51
XS Rating Curve= 0 ,0
Exp/Cntr(USF)=0,0
Exp/Cntr=0.3,0.1

Type RM Length L Ch R = 1 ,16820   ,314.1,319.9,322.3
XS GIS Cut Line= 2
1667883.79510166522116.3720938531668322.01952027522231.836816818
#Sta/Elev= 30
       0  932.39     2.4  932.19     5.8  930.53      16  921.06    22.8   916.3
    26.2  914.82    47.4  908.14    70.3  902.65   141.5  894.37   202.6  891.21
   227.4  891.59   229.8  891.34  235.76888.9649   250.1  887.47   260.3  887.69
  269.12888.9652   305.2  890.98   307.8  891.67     318  898.26   332.1  905.54
     347  917.98   356.2  928.16   368.9  939.37   375.6   947.7   382.4  954.56
   392.6  961.33   406.2  972.45   426.1  982.68   443.5   996.5   453.2 1002.07
#Mann= 5 ,-1,0
       0      .1       0      70     .05       0     220      .1       0
  235.76    .045       0  269.12      .1       0
Bank Sta=235.76,269.12
XS Rating Curve= 0 ,0
Exp/Cntr(USF)=0,0
Exp/Cntr=0.3,0.1

Type RM Length L Ch R = 1 ,16500   ,342.4,341.7,333.2
XS GIS Cut Line= 6
1667821.45634915522369.0260551341667943.64396742522420.884917751
1668010.98208734522453.9094580111668100.76570043522497.942178339
1668169.04509142522529.0464468451668255.98422201522551.821007594
#Sta/Elev= 30
       0  915.03     2.6  913.13     6.1   912.1    27.5  910.58    31.1   909.1
    52.5  894.19    66.7  889.78    84.5  888.46   166.1  889.98   229.5  889.86
   233.1  889.15  237.59886.6996   242.1  885.33   252.9  885.12     266  885.23
  276.58 886.701   298.9  889.28   305.9  892.52   313.5  897.75   327.9  910.81
   338.7  924.35   356.7   945.3   360.3  949.19   363.9  951.82     382  959.38
     399   963.9   415.9  971.67   432.9  980.69     460  997.83   472.6 1004.44
#Mann= 5 ,-1,0
       0      .1       0      70     .05       0  202.74      .1       0
  237.59    .045       0  276.58      .1       0
Bank Sta=237.59,276.58
XS Rating Curve= 0 ,0
Exp/Cntr(USF)=0,0
Exp/Cntr=0.3,0.1

Type RM Length L Ch R = 1 ,16158   ,94.7,98.9,101.2
XS GIS Cut Line= 4
1667721.13520332522672.9726411381667927.02994722522762.575190062
 1668091.7819402522810.8808785421668237.37938132522767.331007248
#Sta/Elev= 30
       0  953.97     4.6  951.17    11.5  944.89    26.4  927.76    54.7  909.57
    83.7  895.63    97.7  893.39   122.7  891.17   194.3  888.91     264  888.01
   277.7  886.83   308.5  886.03  328.96 884.662   339.2  882.62   346.1  882.44
   356.3  883.16  358.69884.6599   359.7  885.31   366.6  893.31   373.4  899.63
   376.8   901.9   393.9  910.63   404.7  919.68     411  924.16   425.4  931.07
   447.9  946.43   469.3  958.59   516.3   974.2   530.9  978.17   548.2  981.89
#Mann= 7 ,-1,0
       0      .1       0      20     .06       0  274.55      .1       0
  304.55     .06       0  328.96    .045       0  358.69     .06       0
  374.55      .1       0
#XS Ineff= 2 , 0
          269.03  893.74
Permanent Ineff=
       F       F
Bank Sta=328.96,358.69
XS Rating Curve= 0 ,0
Exp/Cntr(USF)=0,0
Exp/Cntr=0.3,0.1

Type RM Length L Ch R = 1 ,16059   ,575.7,573.6,567.1
XS GIS Cut Line= 6
1667705.84942094522741.5540169971667838.88701157522790.970208989
1667953.24887886522856.0476806711668051.67802502 522911.43454305
1668119.31127462522879.4200541361668315.03559982 522812.55000727
#Sta/Elev= 30
       0  916.76     6.9  914.04    31.9  901.47    39.2  899.75    97.9  896.78
   108.1  895.73   125.8  892.54   170.2  890.09   196.3  889.32   286.9  889.41
   294.4  888.26   305.7  885.07   328.3  884.26   343.3  881.72   350.7  882.12
  356.65  884.24   365.9  891.53   369.7  893.84   373.5  894.81   458.4  898.59
   464.5  901.36   470.5  905.64   485.3  917.45   492.2     924   495.7  926.16
   532.5  937.77   568.5  950.42   619.9   962.9   641.3  966.66   668.1  974.33
#Mann= 5 ,-1,0
       0      .1       0      60     .06       0   328.3    .045       0
  356.65     .06       0  531.27      .1       0
Bank Sta=328.3,356.65
XS Rating Curve= 0 ,0
Exp/Cntr(USF)=0,0
Exp/Cntr=0.3,0.1