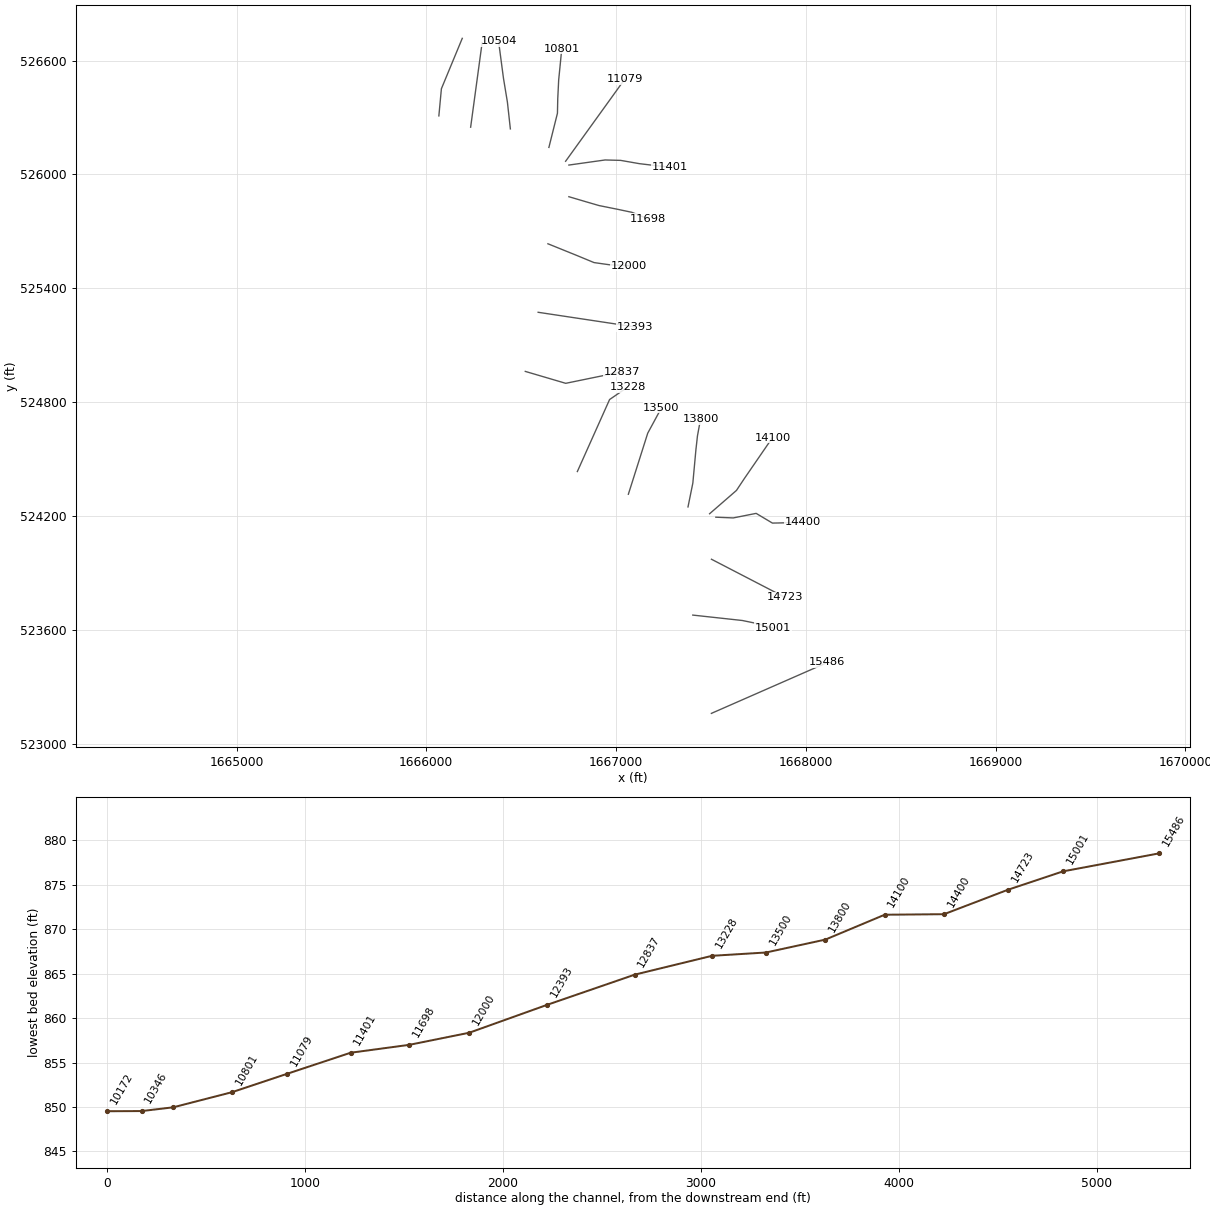
HEC-RAS study WlfRn.prj: WlfRn

--- WlfRn.g01 (geometry) --- (continued)

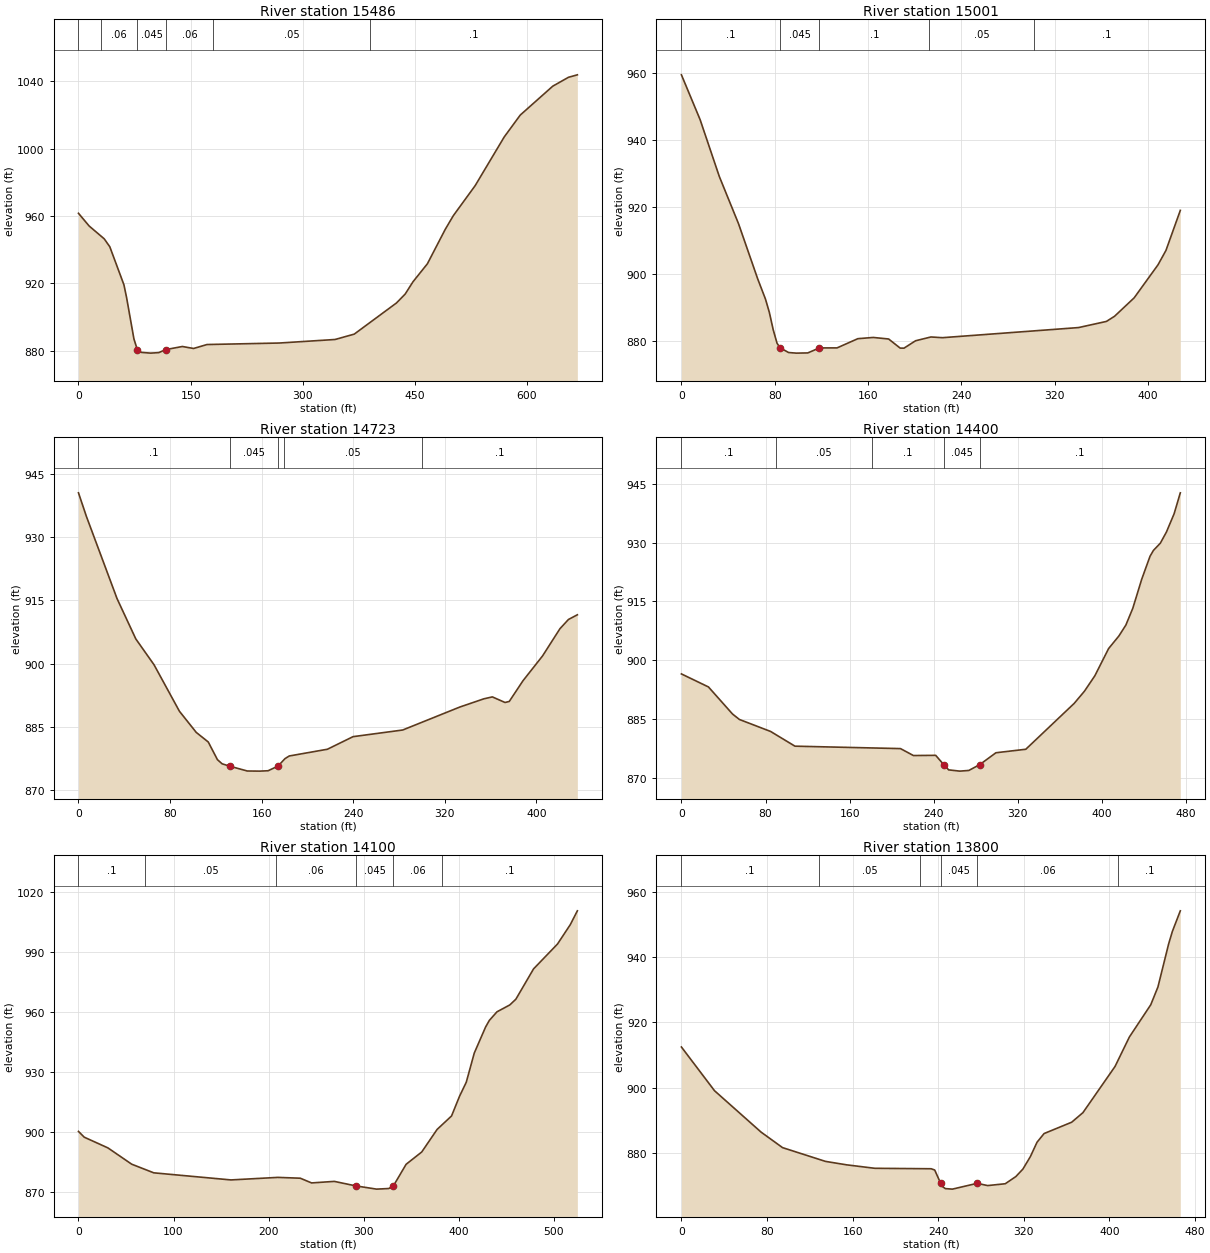
Type RM Length L Ch R = 1 ,15486   ,493,484.5,474.6
XS GIS Cut Line= 2
1667502.39357752 523160.024761511668113.56396651523428.122737248
#Sta/Elev= 30
       0  961.65    14.2  954.12    34.4  946.48    41.9  941.75    60.8  919.14
    64.3  911.67    74.2  886.9278.71996 880.588    84.2  878.96    96.6  878.53
   107.4  878.83116.6399880.6282     139  882.47     154  881.29   171.9  883.64
   268.6  884.53   343.2  886.63   368.9  889.82   425.4  908.34     437  913.61
   447.6     921   466.8  931.66   490.7  952.13   501.5  960.26   530.6  978.02
   569.5 1006.98     591 1020.02   634.5  1037.2   655.5 1042.47   667.4 1043.94
#Mann= 6 ,-1,0
       0      .1       0      30     .06       078.71996    .045       0
116.6399     .06       0     180     .05       0     390      .1       0
Bank Sta=78.71996,116.6399
XS Rating Curve= 0 ,0
Exp/Cntr(USF)=0,0
Exp/Cntr=0.3,0.1

Type RM Length L Ch R = 1 ,15001   ,282.3,278.3,270.7
XS GIS Cut Line= 6
 1667404.3752257523677.9254288861667491.35995986523668.446445216
1667565.91853779523660.3214614731667665.33008436 523649.48847789
1667739.11307328523634.2437577291667825.85568195523610.027926896
#Sta/Elev= 30
       0   959.4      16  946.07    32.5  929.11      49  915.03    65.5  898.55
    72.1  892.59    75.4  888.66    78.7   883.5      82  879.45   84.67878.0908
    91.9  876.69    98.5  876.51   108.4  876.57   118.3  878.06   133.5  878.07
   151.3  880.81   164.5  881.18   177.7  880.72   187.6  878.01   190.9  877.99
   200.8  880.19     214  881.32   223.9  881.11   340.6  884.12   364.5  885.95
   371.5  887.49   388.3  892.97   408.8  902.83   415.6  907.11   427.9  919.03
#Mann= 5 ,-1,0
       0      .1       0   84.67    .045       0   118.3      .1       0
   212.5     .05       0   302.5      .1       0
Bank Sta=84.67,118.3
XS Rating Curve= 0 ,0
Exp/Cntr(USF)=0,0
Exp/Cntr=0.3,0.1

Type RM Length L Ch R = 1 ,14723   ,323.5,323,321.3
XS GIS Cut Line= 2
  1667502.772959523972.2353657951667889.83077658523771.679649381
#Sta/Elev= 30
       0  940.57     6.9  934.98    33.7  915.43    50.1  905.85      66  899.72
    88.2  888.67   102.9  883.64   113.4  881.36   121.4  877.17   125.5  876.18
  131.99875.6274   147.5  874.47   158.4  874.44   165.7  874.53  174.28875.6263
   180.5  877.42   184.2  878.04   217.5  879.64   239.9  882.63   283.3  884.21
   333.2  889.67   354.2  891.62   361.6  892.08   372.7  890.75   376.4     891
   388.4  895.92   405.5  901.82   420.7  908.29   428.1  910.47   435.9  911.59
#Mann= 5 ,-1,0
       0      .1       0  131.99    .045       0  174.28      .1       0
     180     .05       0     300      .1       0
Bank Sta=131.99,174.28
XS Rating Curve= 0 ,0
Exp/Cntr(USF)=0,0
Exp/Cntr=0.3,0.1

Type RM Length L Ch R = 1 ,14400   ,272.6,300,327.6
XS GIS Cut Line= 5
1667525.88035103524193.7934972071667617.45279988524189.978524873
1667738.17357785524213.9643368421667824.05529584524162.735764757
1667983.83764468524166.257524723
#Sta/Elev= 30
       0   896.5    25.7  893.18    48.6  886.27    55.2  884.87    84.8  881.82
     108  878.06   208.4  877.44   220.7  875.67   241.9  875.72   249.5  873.36
   254.2  872.01   264.8  871.69   273.4  871.86   283.9  873.37   299.2  876.38
   327.6  877.27   373.6  888.97   383.4  892.09   393.3  896.03   406.4  902.98
   416.2   906.2   422.8  908.97   429.4  913.26   437.9  920.69   445.8  926.54
     449  928.02   455.6  929.88   461.4  932.73   468.7  937.38   474.6  942.73
#Mann= 5 ,-1,0
       0      .1       0      90     .05       0  181.65      .1       0
   249.5    .045       0   283.9      .1       0
Bank Sta=249.5,283.9
XS Rating Curve= 0 ,0
Exp/Cntr(USF)=0,0
Exp/Cntr=0.3,0.1

Type RM Length L Ch R = 1 ,14100   ,289.5,300,309
XS GIS Cut Line= 6
 1667493.0009952524211.9783383061667634.53434943524334.941785172
1667676.03721917524397.4232875111667732.68966493524479.827978343
1667775.17940934524541.6310043341667824.75050442 524613.73486276
#Sta/Elev= 30
       0  900.49       6  897.62      31  892.24      56   884.1    79.2  879.78
   160.5  876.23   209.8   877.5   233.4  877.09   245.3  874.73   269.2   875.5
  291.97873.2334   313.7  871.63   326.5  871.93  331.38873.2352   344.8  884.05
   361.2  890.19   377.4  901.48   392.6  908.21     401  918.07   408.1  925.09
   416.5  939.65   428.4  952.66   432.4  956.02   440.4  960.29   453.9  963.73
   460.3  966.61   478.9  981.75   504.1  994.19   517.6 1003.91     525 1010.79
#Mann= 6 ,-1,0
       0      .1       0      70     .05       0  207.49     .06       0
  291.97    .045       0  331.38     .06       0   382.5      .1       0
Bank Sta=291.97,331.38
XS Rating Curve= 0 ,0
Exp/Cntr(USF)=0,0
Exp/Cntr=0.3,0.1

Type RM Length L Ch R = 1 ,13800   ,304.5,300,290.1
XS GIS Cut Line= 6
1667379.12687308524247.9473790691667404.65390368524373.755683929
1667411.53217076524448.4395896791667420.70308417524548.018130675
1667429.01441926524622.5701469181667444.81983384524708.985000342
#Sta/Elev= 30
       0  912.43    30.9  899.03    74.4  886.33    94.5  881.56   134.6  877.34
   154.2  876.29   180.7  875.22   233.4  875.08   236.7  874.68  242.27870.5881
   243.3  869.78   246.6  868.99   253.2  868.83   276.3   870.6   286.2  869.92
   302.6  870.48   312.5  872.68   319.1  874.98   326.1  878.82   332.3  883.21
   338.9  885.88   364.7  889.36   375.2  892.29   405.2  906.46   418.6   915.5
   438.6   925.4   445.3  930.86   455.3  944.07   458.8  947.91   466.2  954.21
#Mann= 6 ,-1,0
       0      .1       0  128.37     .05       0  223.37     .06       0
  242.27    .045       0   276.3     .06       0  408.39      .1       0
Bank Sta=242.27,276.3
XS Rating Curve= 0 ,0
Exp/Cntr(USF)=0,0
Exp/Cntr=0.3,0.1

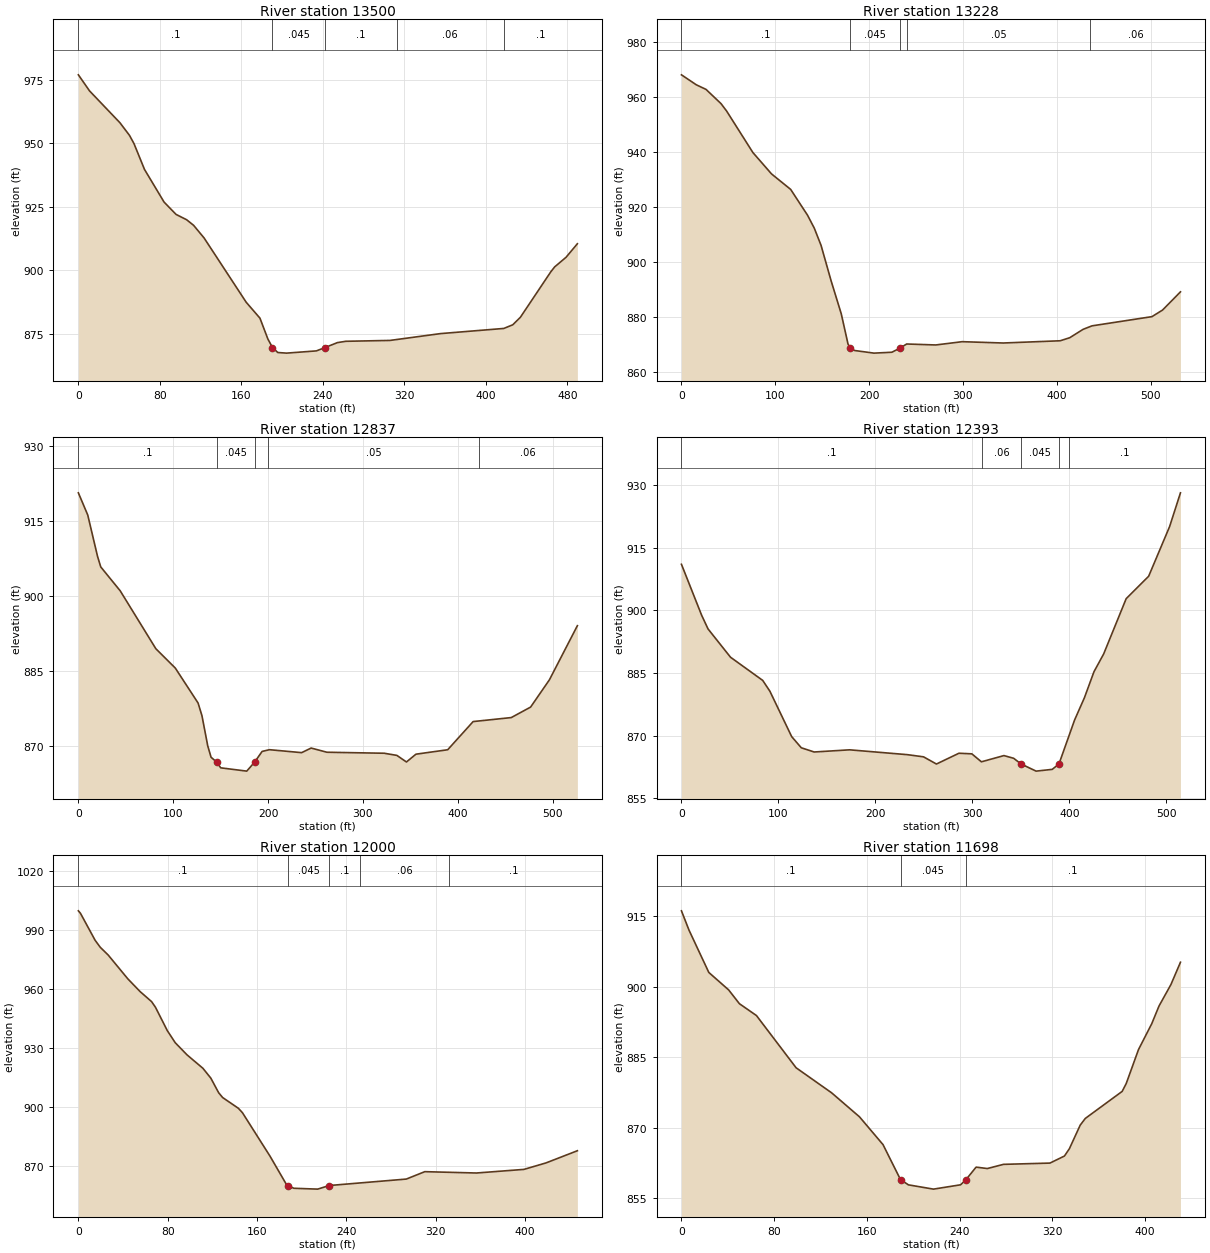
Type RM Length L Ch R = 1 ,13500   ,273.8,271.8,267.7
XS GIS Cut Line= 6
 1667064.8294521524314.804686338 1667091.3389135524398.192314833
1667114.00684717524469.6846259241667144.23152426524565.007926092
1667166.89912984524636.5002371671667239.43245754524770.357007693
#Sta/Elev= 30
       0  976.98      11  970.64    40.8  958.11    50.2  953.12    54.6  949.88
    64.9  939.73    84.1  926.87    95.9     922   106.2  919.92   113.1  917.71
   123.4  912.72   164.7  887.42   178.2  881.15     186  872.92  190.51869.5845
   195.7  867.62   204.3  867.38   233.6  868.26  242.09 869.584   254.2  871.52
   262.5  872.04   305.8  872.38   355.4  875.07   417.5   877.1   426.3  878.54
   433.8  881.51   463.6  899.39   467.4  901.33   478.6  905.13   489.7  910.45
#Mann= 5 ,-1,0
       0      .1       0  190.51    .045       0  242.09      .1       0
   312.5     .06       0   417.5      .1       0
Bank Sta=190.51,242.09
XS Rating Curve= 0 ,0
Exp/Cntr(USF)=0,0
Exp/Cntr=0.3,0.1

Type RM Length L Ch R = 1 ,13228   ,425.2,390.9,362.3
XS GIS Cut Line= 3
1666796.08604715524434.4596067751666965.90405855524813.832519927
1667061.64003686524879.591878863
#Sta/Elev= 30
       0  967.94    15.8  964.33    26.2  962.65    42.2  957.48    48.1  954.82
    76.1  939.77      96     932   116.4  926.38   134.4  917.01   141.6   912.3
   148.8  906.07   159.5  893.22   170.3  881.28   177.5  870.32  179.96868.7803
   184.7  867.95   205.2  867.01   224.2  867.33  232.67868.7783     240  870.32
     271  869.97   299.2  871.16   342.9  870.68   403.6  871.49   413.8   872.6
     428  875.63   437.5   876.9   501.4  880.24   512.7  882.63   531.8  889.23
#Mann= 5 ,-1,0
       0      .1       0  179.96    .045       0  232.67      .1       0
     240     .05       0  435.65     .06       0
Bank Sta=179.96,232.67
XS Rating Curve= 0 ,0
Exp/Cntr(USF)=0,0
Exp/Cntr=0.3,0.1

Type RM Length L Ch R = 1 ,12837   ,433.5,444.6,442.8
XS GIS Cut Line= 3
1666521.68331153524962.0392636411666734.82943678524899.286440547
1667032.55976786524960.450670469
#Sta/Elev= 30
       0   920.6     9.9  916.16    20.2  907.89    23.6  905.77    44.1  900.99
    81.7  889.39   102.2  885.52   126.2  878.53   130.3  875.99   136.4  869.95
   139.9  867.67  145.68866.7286   150.1  865.55   177.5  864.89  185.85866.6971
   193.7  868.83   201.4  869.18   235.4  868.59   245.4  869.51   262.1  868.67
   322.4  868.47   335.8  868.04   345.9  866.72   355.9  868.28   389.4  869.17
   416.2  874.81   456.4  875.61   476.8  877.71   496.6  883.16   526.1     894
#Mann= 5 ,-1,0
       0      .1       0  145.68    .045       0  185.85      .1       0
     200     .05       0  422.19     .06       0
Bank Sta=145.68,185.85
XS Rating Curve= 0 ,0
Exp/Cntr(USF)=0,0
Exp/Cntr=0.3,0.1

Type RM Length L Ch R = 1 ,12393   ,396.3,392.4,389.9
XS GIS Cut Line= 2
1666589.40693084525273.6147428731667098.38570163525196.863975849
#Sta/Elev= 30
       0     911    20.8  898.81    27.4  895.53    50.6  888.75    83.8   883.2
    91.2  880.62   113.7  869.74   123.6  867.07   136.9  866.06   173.4  866.58
   233.1  865.42   249.7   864.9     263  863.18   286.2  865.76   299.5  865.62
   309.4  863.71   332.6   865.2   342.6  864.56  350.41863.1774   365.8  861.48
   382.4   861.9  389.37863.1796   405.5  873.72   415.6  879.03   425.5  885.28
   435.5  889.54   458.7  902.77   481.9  908.14   503.5  920.03   514.7  928.11
#Mann= 5 ,-1,0
       0      .1       0     310     .06       0  350.41    .045       0
  389.37     .06       0     400      .1       0
Bank Sta=350.41,389.37
XS Rating Curve= 0 ,0
Exp/Cntr(USF)=0,0
Exp/Cntr=0.3,0.1

Type RM Length L Ch R = 1 ,12000   ,295.3,302.8,307.3
XS GIS Cut Line= 6
1666640.99466984525634.6376765821666722.10605617525601.816876084
1666791.62986726525573.6847145111666884.05225459 525535.49220559
1666966.22761518525523.8961001781667067.74611293525519.332132921
#Sta/Elev= 30
       0  999.57     1.9   998.3      15  984.64    19.6  981.08    26.7  977.15
    44.3  965.07    55.3  958.61    65.6   953.5    69.1  950.63    79.7  938.77
    86.8  932.64    97.4  926.46   111.6  919.66   118.7  914.66   125.7  907.26
   129.3  904.81   143.4  899.36     147  897.14   171.8     875     186  861.12
  187.68  860.18   193.1  858.78   214.4  858.35  224.83860.1824   293.8  863.45
   310.4  867.21   356.7  866.53   399.2  868.36     419  871.65   447.1  877.83
#Mann= 5 ,-1,0
       0      .1       0  187.68    .045       0  224.83      .1       0
   252.5     .06       0   332.5      .1       0
Bank Sta=187.68,224.83
XS Rating Curve= 0 ,0
Exp/Cntr(USF)=0,0
Exp/Cntr=0.3,0.1

Type RM Length L Ch R = 1 ,11698   ,270.1,296.7,271
XS GIS Cut Line= 6
1666751.30776942525882.6949232521666836.41947584525857.536180928
1666910.07057525525836.0450821671667009.49590135525816.064479083
1667082.97049193525800.514641419  1667165.202939525767.665953845
#Sta/Elev= 30
       0   916.2     6.5   912.1    23.6  903.09    40.7  899.38      50  896.44
    64.7  893.92    98.9  882.81   129.6  877.47   153.6  872.37   173.9  866.46
  188.97 859.017   195.8   857.9   217.4  856.99   240.8  857.91  245.47859.0163
   254.2  861.67   263.9  861.37   277.8  862.26   317.9  862.53   330.4  864.03
   334.7   865.6     344   870.6   348.4  872.03   380.2  877.78   383.7  879.45
   394.3  886.68   405.7  892.17     412  895.95   422.3  900.53   430.5  905.26
#Mann= 3 ,-1,0
       0      .1       0  188.97    .045       0  245.47      .1       0
Bank Sta=188.97,245.47
XS Rating Curve= 0 ,0
Exp/Cntr(USF)=0,0
Exp/Cntr=0.3,0.1

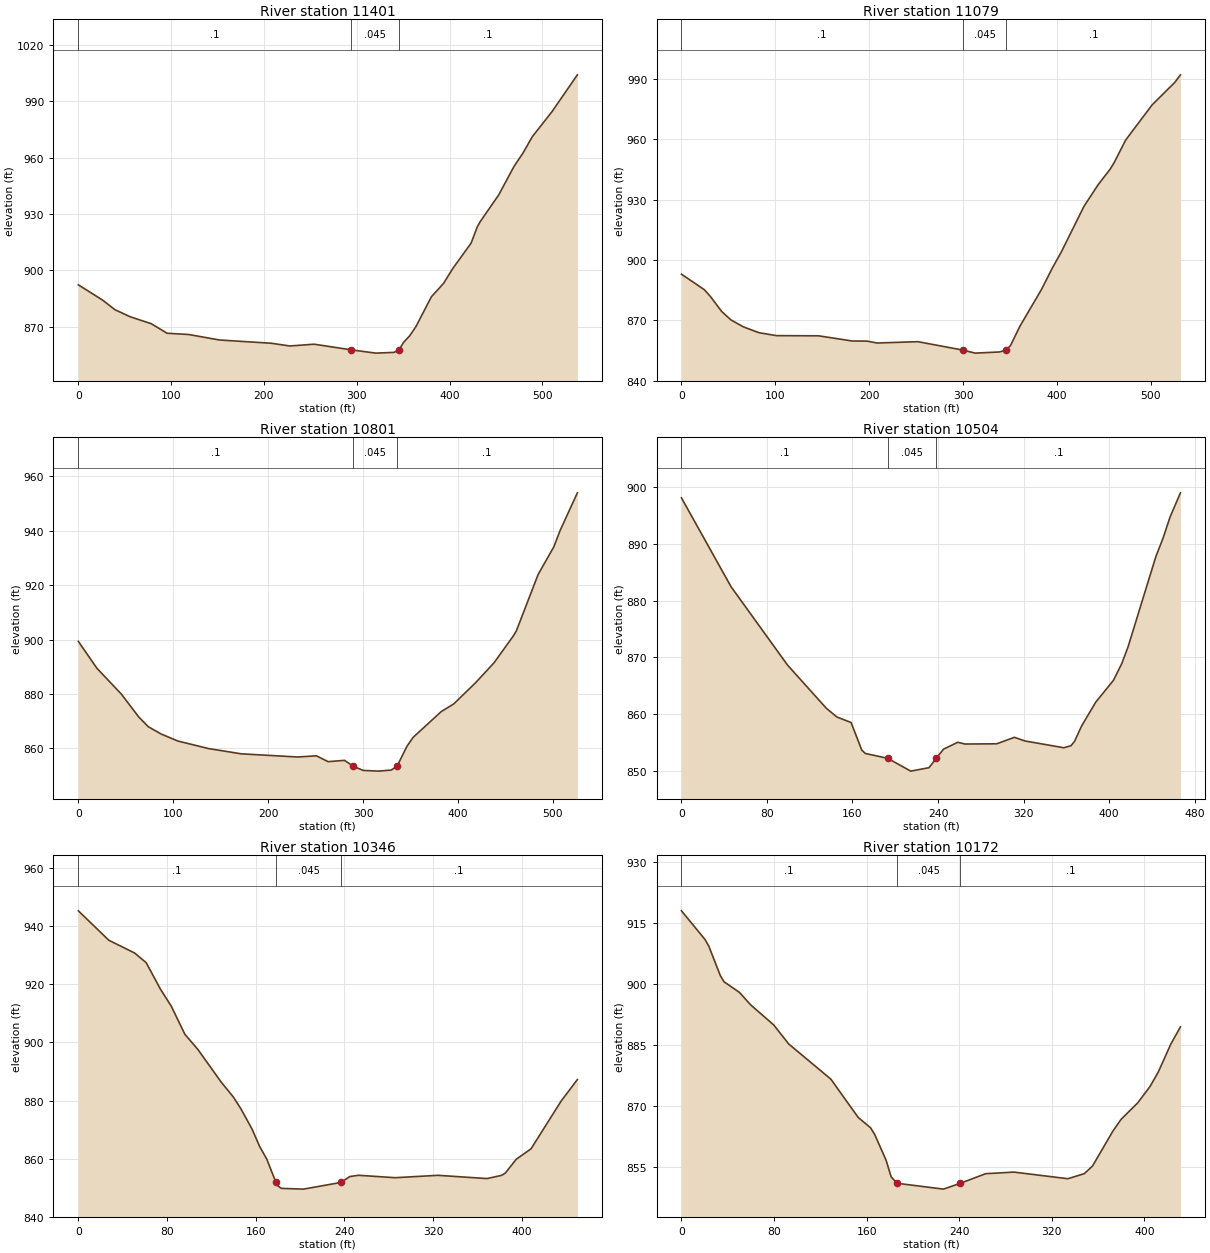
Type RM Length L Ch R = 1 ,11401   ,292.1,322,346.9
XS GIS Cut Line= 6
1666751.38062039526049.4342630131666942.18238768526076.273604333
1667024.03655468526074.0793830011667122.55505842526056.858616918
1667197.26291426526047.8858658371667284.75913034526038.375386178
#Sta/Elev= 30
       0  892.38    26.1  884.27    39.4  879.18    55.9   875.4    78.5  871.74
    95.7  866.65   118.9  865.99     152  863.08   208.2  861.34   227.9  859.89
   254.1  860.84  294.12857.8433   320.5   856.1   340.2   856.5  345.64857.8453
   350.4  861.76   357.1  865.31   363.7  870.09   380.4  885.98   393.6  893.16
   403.7  901.18   423.3  914.54   429.9  923.14   433.2  926.01     453  940.11
   469.5  955.24   479.4  962.53   489.3   971.1   510.5  984.38   537.8 1003.91
#Mann= 3 ,-1,0
       0      .1       0  294.12    .045       0  345.64      .1       0
Bank Sta=294.12,345.64
XS Rating Curve= 0 ,0
Exp/Cntr(USF)=0,0
Exp/Cntr=0.3,0.1

Type RM Length L Ch R = 1 ,11079   ,259.3,277.4,283.9
XS GIS Cut Line= 3
1666734.15546045526069.4382894841666992.34961018526427.690880507
1667044.91905884526500.896114677
#Sta/Elev= 30
       0  892.97    24.4  885.24      31   881.8    42.7  874.51    52.7  870.24
    66.2  866.73    82.7  863.86   101.3  862.41   146.1  862.32   182.1  859.74
   197.8  859.69   208.4  858.75   251.9  859.41  299.72855.2449     313  853.72
   338.8   854.3  346.15855.2447   350.6   857.5   360.6  867.07   383.5  885.27
   395.2  896.03   404.6  903.88   428.8  926.61     444  937.45   457.1  945.37
   461.2  948.55   473.3  959.62   501.5  977.11   525.8  988.36   531.7  992.05
#Mann= 3 ,-1,0
       0      .1       0  299.72    .045       0  346.15      .1       0
Bank Sta=299.72,346.15
XS Rating Curve= 0 ,0
Exp/Cntr(USF)=0,0
Exp/Cntr=0.3,0.1

Type RM Length L Ch R = 1 ,10801   ,288.6,297,295.9
XS GIS Cut Line= 6
1666646.13378225526142.4345921121666691.15861151526322.652376667
1666692.72028817526397.6361505841666697.60184009526497.556554422
1666705.14053893526572.9038446691666713.91512768526661.879388511
#Sta/Elev= 30
       0  899.32    19.6  889.42    45.3  879.97    63.5  871.61    73.7  867.97
    87.2   865.3   104.9  862.71   137.3  859.94   171.8  858.01   231.1  856.85
   250.9  857.28   263.2  855.14   280.5  855.62  289.77853.4413   300.2  851.92
   316.4  851.66   329.7  852.05  335.87853.4419   346.2  860.73   352.7  864.03
   382.4  873.52   395.6  876.35   418.7  884.16   438.2  891.51   458.2  901.22
   461.5   903.1   484.6  923.94   501.1  934.06   507.7  940.04   525.9  953.89
#Mann= 3 ,-1,0
       0      .1       0  289.77    .045       0  335.87      .1       0
Bank Sta=289.77,335.87
XS Rating Curve= 0 ,0
Exp/Cntr(USF)=0,0
Exp/Cntr=0.3,0.1

Type RM Length L Ch R = 1 ,10504   ,164.2,158.7,149.4
XS GIS Cut Line= 4
1666443.04366603526240.0254453451666427.42241728526381.324302263
1666406.82089561526506.1452865281666380.76859726 526702.55199234
#Sta/Elev= 30
       0  898.15    46.4  882.48    99.2  868.67   135.5  861.05   145.4  859.51
   158.7  858.53   168.7  853.66     172  853.08  192.92852.2204   214.5  849.96
   231.6  850.57   238.3852.2217   245.2  853.84   258.5  855.05   265.1  854.74
   294.9  854.78   311.5  855.92   321.3  855.28   357.8  854.08   364.4  854.45
   367.7  855.21   374.3  857.91   387.6  862.14   404.1  865.97   411.9  868.93
   417.8  871.89   443.8   887.8   450.5  891.04   457.1  894.79   466.8  899.04
#Mann= 3 ,-1,0
       0      .1       0  192.92    .045       0   238.3      .1       0
Bank Sta=192.92,238.3
XS Rating Curve= 0 ,0
Exp/Cntr(USF)=0,0
Exp/Cntr=0.3,0.1

Type RM Length L Ch R = 1 ,10346   ,177.4,173.9,162.6
XS GIS Cut Line= 2
1666233.72436909526248.978968813 1666294.3170799526694.941320362
#Sta/Elev= 30
       0  945.28    27.5  935.15    50.7  930.78    61.2  927.44    73.9  918.42
    83.8  912.48    96.1  902.79   107.8   897.6   128.9  886.33   139.9  881.19
   146.7  877.12   156.7  870.18   163.3  864.38   169.9  859.89  178.22851.8507
   179.8   850.7   183.1   849.8     203  849.54  236.95851.8506   244.8  853.87
   252.7   854.3   285.8  853.47   324.3  854.29   368.6  853.17   381.8  854.28
   385.1  855.07     395  859.82   408.3  863.41   435.4  879.81   450.1  887.23
#Mann= 3 ,-1,0
       0      .1       0  178.22    .045       0  236.95      .1       0
Bank Sta=178.22,236.95
XS Rating Curve= 0 ,0
Exp/Cntr(USF)=0,0
Exp/Cntr=0.3,0.1

Type RM Length L Ch R = 1 ,10172   ,315.3,322.9,320.7
XS GIS Cut Line= 3
1666066.24580357526308.5167357121666079.62025724526451.611846801
1666189.59455609526717.214122118
#Sta/Elev= 30
       0     918    20.3  910.97    23.6  909.34    33.5  902.12    36.8  900.54
      50  897.96    59.8  894.86    79.6  889.96    92.8  885.21   129.1  876.59
   152.8  867.14   163.4  864.62     167  862.96   176.8  856.66   181.2  852.56
  186.25 850.962   226.4  849.52     241850.9629   262.9  853.32   287.3  853.71
   333.9  852.08   348.1  853.33   355.2   855.2   372.7  863.75     380  866.73
   394.2  870.73   404.9  874.77     412  878.31   422.9  885.23   431.2  889.45
#Mann= 3 ,-1,0
       0      .1       0  186.25    .045       0     241      .1       0
Bank Sta=186.25,241
XS Rating Curve= 0 ,0
Exp/Cntr(USF)=0,0
Exp/Cntr=0.3,0.1