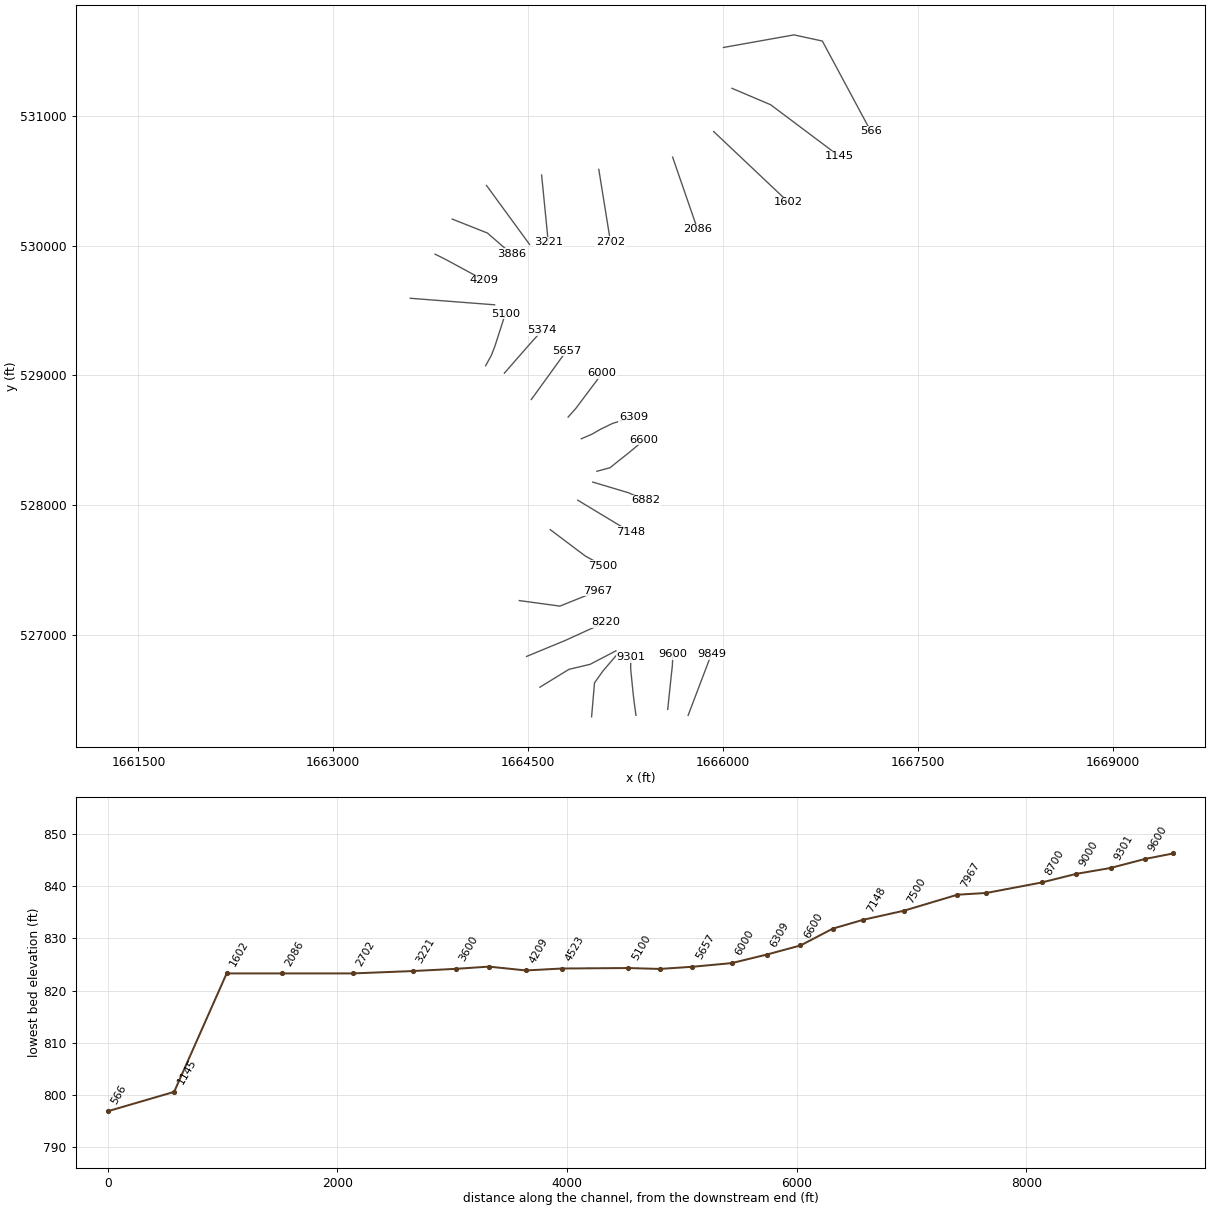
HEC-RAS study WlfRn.prj: WlfRn

--- WlfRn.g01 (geometry) --- (continued)

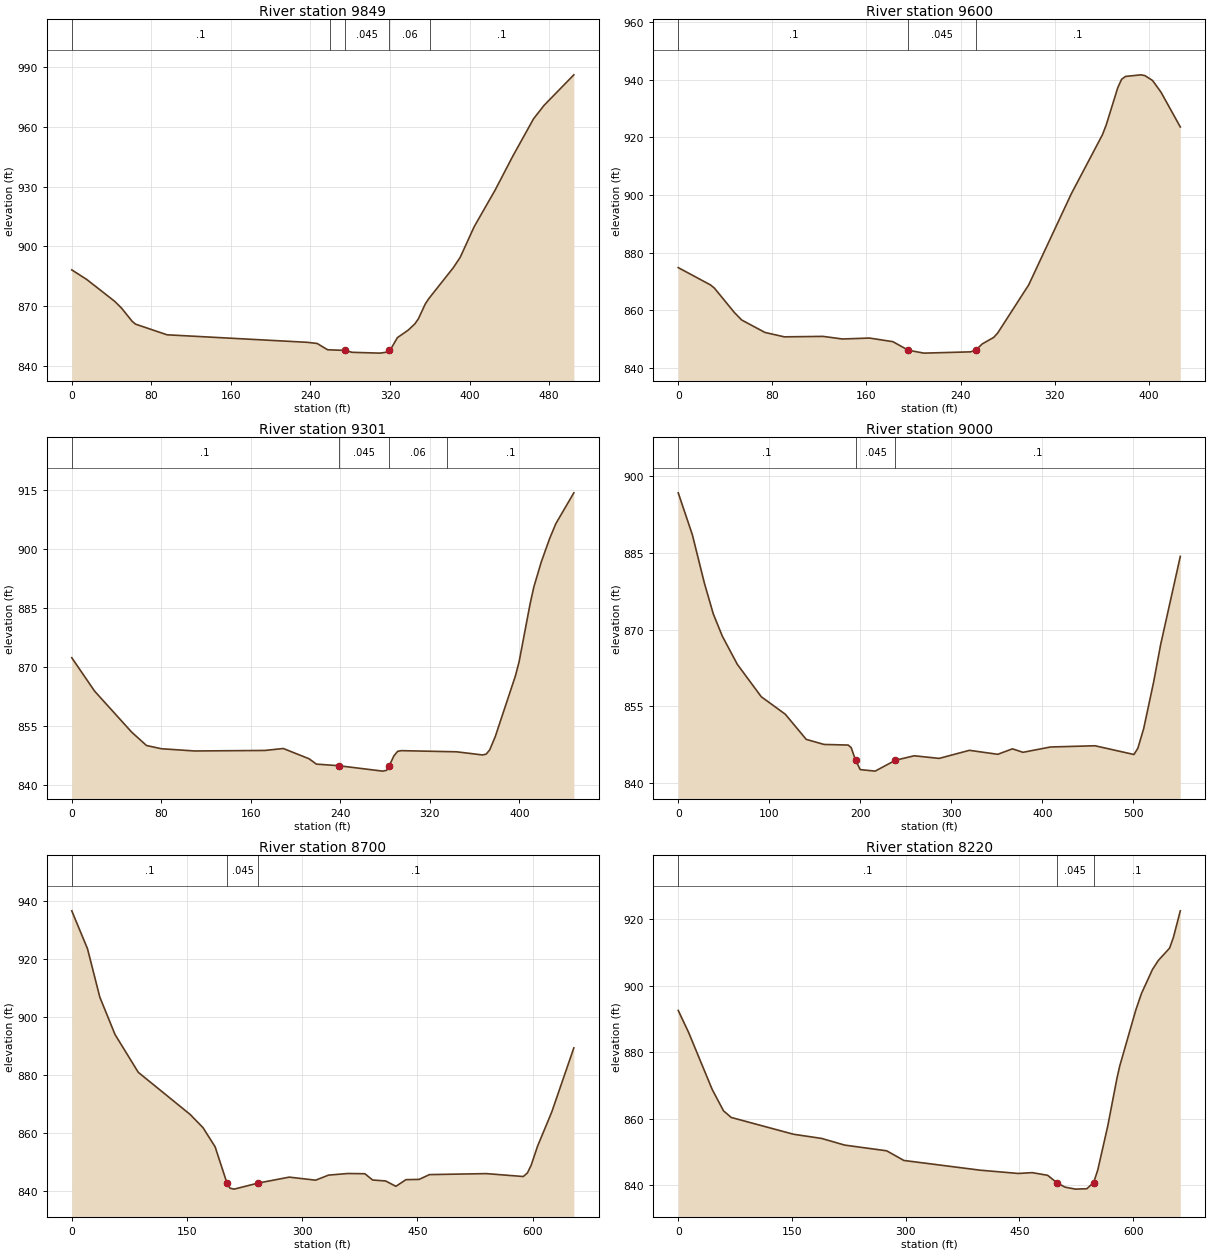
Type RM Length L Ch R = 1 ,9849    ,236,248.8,244.6
XS GIS Cut Line= 2
1665731.53747188526383.5467132361665910.73325156526855.479051844
#Sta/Elev= 30
       0  888.12    15.1  883.29    43.2  872.31    50.2  868.82    60.7  862.28
    64.2  860.84    95.8   855.5   236.6  851.73   246.7  851.15   257.2  847.99
   274.8  847.65   281.8   846.7   309.9  846.29   316.9  846.79  319.43847.7103
   320.6  848.21   327.4  854.07   338.4   857.9     345  861.03   348.5  863.54
   355.5  871.07     359  873.69   383.6  889.22   390.6  894.49   404.6  909.83
   425.7  928.26   443.2  945.07   464.3  964.05   474.8  970.77   504.8  986.14
#Mann= 5 ,-1,0
       0      .1       0     260     .06       0   274.8    .045       0
  319.43     .06       0     360      .1       0
Bank Sta=274.8,319.43
XS Rating Curve= 0 ,0
Exp/Cntr(USF)=0,0
Exp/Cntr=0.3,0.1

Type RM Length L Ch R = 1 ,9600    ,293,299.4,305.6
XS GIS Cut Line= 6
1665574.40461142526429.3559034171665583.49678484526516.382304177
1665591.29007635526590.9759870021665601.70114475526690.432809085
1665610.06628551526765.5629081731665613.89304951526854.323557422
#Sta/Elev= 30
       0  874.85    27.5  868.84    30.8  867.73    47.7  859.31    53.9  856.72
    73.7  852.39    90.2  850.86   123.2  851.02   139.6  850.12   162.7  850.44
   182.5  849.19   195.7  846.21   208.9  845.22   248.5  845.66  253.05  846.27
   258.4  848.38   268.3  850.69   271.6  852.18     298  868.87   334.3   900.5
   360.6  920.82   363.9  924.28   373.7  937.17     377  940.11   380.3  941.09
   393.5  941.65   396.8  941.38   403.3  939.69   410.5  935.63   426.9  923.58
#Mann= 3 ,-1,0
       0      .1       0   195.7    .045       0  253.05      .1       0
Bank Sta=195.7,253.05
XS Rating Curve= 0 ,0
Exp/Cntr(USF)=0,0
Exp/Cntr=0.3,0.1

Type RM Length L Ch R = 1 ,9301    ,300.9,300.6,294.6
XS GIS Cut Line= 6
1665330.10775593 526384.000837411665314.86976865526493.681077935
1665306.55744932526568.2239078511665296.60700991526667.727645852
1665289.14409832526742.3554493561665290.33996207526830.411703683
#Sta/Elev= 30
       0  872.31    20.4  863.83    53.5  853.42    66.8  850.01      80  849.19
   109.8  848.62   172.6  848.75   189.1  849.25   212.1  846.64   218.7  845.28
   238.5  844.88   277.9   843.5   281.4   843.7  283.66   844.8     288   847.4
   291.3  848.53   294.6   848.7     344  848.41   367.1  847.61   370.4  847.81
   373.6   848.9   378.6  852.31   396.6  867.72   399.9  871.33   409.7  885.99
     413  890.24   419.6  896.56   427.1  902.54   432.7  906.37   448.8   914.2
#Mann= 4 ,-1,0
       0      .1       0   238.5    .045       0  283.66     .06       0
  335.74      .1       0
Bank Sta=238.5,283.66
XS Rating Curve= 0 ,0
Exp/Cntr(USF)=0,0
Exp/Cntr=0.3,0.1

Type RM Length L Ch R = 1 ,9000    ,307.4,300,261.3
XS GIS Cut Line= 6
1664988.42349993526372.3691407591664995.87492859526459.551053002
1665002.26205492526534.2789219171665010.77778593526633.915533677
1665075.09622684526724.4747357521665190.92377779526859.510104222
#Sta/Elev= 30
       0  896.79    15.5   888.6    28.7  879.15    38.5  873.12    48.4  868.77
    64.9  863.25    91.2  856.91   117.6  853.49   140.6  848.57   160.1  847.58
   186.7  847.46     190  846.95  194.82844.4792   199.9  842.66   216.3  842.36
  238.42844.4783   259.2  845.36   286.6  844.85   319.9  846.43     351  845.65
   367.1  846.72   378.7  846.04   408.9  847.08   457.8  847.32   500.6  845.61
   504.9  846.85   511.3   850.7   522.2  859.79   529.9  867.11   551.5  884.36
#Mann= 3 ,-1,0
       0      .1       0  194.82    .045       0  238.42      .1       0
Bank Sta=194.82,238.42
XS Rating Curve= 0 ,0
Exp/Cntr(USF)=0,0
Exp/Cntr=0.3,0.1

Type RM Length L Ch R = 1 ,8700    ,457.9,479.6,457.5
XS GIS Cut Line= 6
1664590.64181517526600.721702427   1664665.21975526646.486374676
1664729.14350668526685.7133303431664814.37561968526738.015063003
1664976.89497967526776.5248285091665175.48577133 526880.14896783
#Sta/Elev= 30
       0  936.54    20.5  923.47    36.5  906.84    56.3  893.96    86.6  880.93
   154.1  866.43   170.8  861.89   186.6  855.29  202.01 842.815   205.9  841.06
   211.3  840.72  242.93 842.822   283.1  844.85   317.4   843.8   334.3  845.55
   359.4   846.1   381.5  846.02   391.6  843.86   408.5  843.53   421.9  841.69
     435  843.98   452.1  844.07   465.6  845.72   539.6  846.06   587.7  845.06
   593.1  846.31     598  848.98   606.2  855.46   624.7  867.24   653.5  889.35
#Mann= 3 ,-1,0
       0      .1       0  202.01    .045       0  242.93      .1       0
Bank Sta=202.01,242.93
XS Rating Curve= 0 ,0
Exp/Cntr(USF)=0,0
Exp/Cntr=0.3,0.1

Type RM Length L Ch R = 1 ,8220    ,254.9,253.1,251
XS GIS Cut Line= 6
1664487.83684316526837.1817437611664787.83481157526961.251900761
1664856.06105307526992.3994762581664947.02970316527033.928920759
1665015.25627274527065.0761681781665094.85388257527101.414022012
#Sta/Elev= 30
       0  892.58    13.6     886    44.8  868.76    59.7  862.33    69.9  860.32
     152  855.26   189.1     854   219.5  851.99   274.9  850.27   297.6  847.36
   398.1  844.43   448.6  843.44   466.7  843.69   487.1  842.89   499.4 840.665
   509.9  839.33   523.8  838.72   538.8  838.84  547.73840.6627   553.2  844.45
   566.3  857.61   578.5  872.06   582.1  875.73   603.4   892.7   610.9   897.7
   625.4  904.93   633.1  907.64     648  911.37     653   914.6   662.1   922.6
#Mann= 3 ,-1,0
       0      .1       0   499.4    .045       0  547.73      .1       0
Bank Sta=499.4,547.73
XS Rating Curve= 0 ,0
Exp/Cntr(USF)=0,0
Exp/Cntr=0.3,0.1

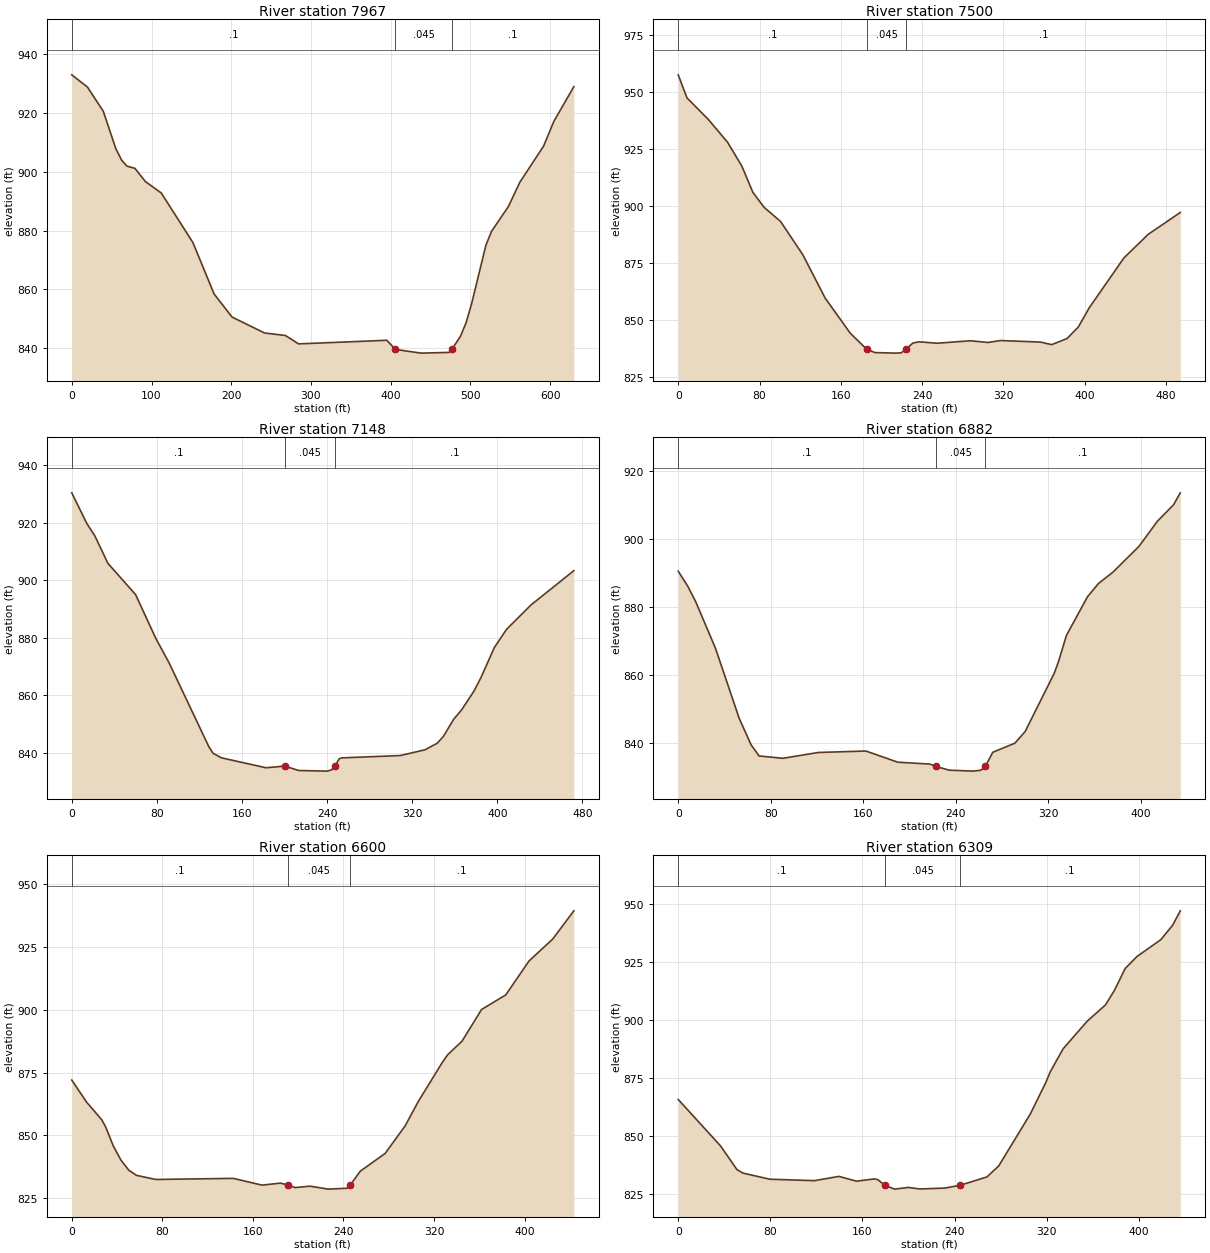
Type RM Length L Ch R = 1 ,7967    ,492.7,467.3,447
XS GIS Cut Line= 3
 1664431.7390952 527267.268173731664744.49935543527224.582003944
1665035.72679057527341.991818076
#Sta/Elev= 30
       0  932.89    19.6  928.75    39.5  920.53    55.3  907.79    62.6  903.88
    69.3  901.87    79.2  901.13    92.4  896.64   112.3  892.75     152   875.9
   178.5  858.47     201  850.63   241.8  845.22   267.9  844.37   284.5  841.52
   395.2  842.74  405.77 839.639     438  838.38   473.1  838.62  476.73839.6398
   487.5   844.1   494.6  848.73   501.7  855.38   519.4  875.02   526.4  879.71
   547.7   888.2   561.8  896.33   591.8   908.7   604.7  917.12   629.7  928.87
#Mann= 3 ,-1,0
       0      .1       0  405.77    .045       0  476.73      .1       0
Bank Sta=405.77,476.73
XS Rating Curve= 0 ,0
Exp/Cntr(USF)=0,0
Exp/Cntr=0.3,0.1

Type RM Length L Ch R = 1 ,7500    ,342.1,351.9,350.9
XS GIS Cut Line= 6
1664670.21285026527813.1651436691664740.14053193527760.568792179
1664800.07873225527715.4862051761664879.99589525527655.376089171
1664939.93376751527610.2935021671665077.26509875527535.230604017
#Sta/Elev= 30
       0  957.62     8.6   947.5    29.7  937.96    48.5  928.01    62.5  917.59
    73.4  906.02    84.4  899.42   100.7  893.18   122.6  878.54   144.6  859.47
   169.3  844.04  185.39 837.053   193.5  835.55   214.4  835.31   219.5  835.48
  224.33837.0511   230.8  839.75   237.2  840.27   254.7  839.66   287.5  840.74
   304.7     840   317.1  840.84   356.3  840.17   367.5  839.04   382.6  841.73
   393.7  846.81   404.3  855.17   438.5  877.14   462.3  887.48     494  897.14
#Mann= 3 ,-1,0
       0      .1       0  185.39    .045       0  224.33      .1       0
Bank Sta=185.39,224.33
XS Rating Curve= 0 ,0
Exp/Cntr(USF)=0,0
Exp/Cntr=0.3,0.1

Type RM Length L Ch R = 1 ,7148    ,245.7,266.1,264.3
XS GIS Cut Line= 2
1664882.08851973528039.961303899 1665286.1467528527795.967344561
#Sta/Elev= 30
       0  930.47      14  919.91    21.7  915.48      34  905.91      60  895.05
    79.1  879.73    91.4  871.35     129     842   132.8  839.82   140.5  838.24
   182.6  834.76   200.5  835.35   213.2  833.81   240.1  833.59   244.3  834.04
  247.25  835.35   251.5  837.91   253.9   838.2   308.8  839.01   332.1  841.02
   343.6  843.31   349.4  845.69   358.9  851.58   366.6  854.98   378.2   861.5
   384.5  866.01   397.2  876.56   408.7  882.93   431.7  891.43     472  903.37
#Mann= 3 ,-1,0
       0      .1       0   200.5    .045       0  247.25      .1       0
Bank Sta=200.5,247.25
XS Rating Curve= 0 ,0
Exp/Cntr(USF)=0,0
Exp/Cntr=0.3,0.1

Type RM Length L Ch R = 1 ,6882    ,242.2,282,293.8
XS GIS Cut Line= 3
1664997.74406572528179.4246022371665272.12074157528097.270742713
1665407.56656104528038.752521978
#Sta/Elev= 30
       0  890.49     8.2  886.11    15.1  881.56    32.2  867.91    52.7  847.36
      63  839.59    69.9  836.34    90.4  835.65   121.2  837.36   162.3  837.78
   189.7  834.51   217.4  833.96  222.92833.2474   234.2  832.17   254.8  831.89
   261.6  832.15  265.42833.2493   271.9  837.41     291  840.08   299.9   843.5
   324.9  860.47   328.5  863.78   335.6   871.7   353.8  883.02   363.3   886.9
   375.8  890.23   398.3  897.79   414.2  905.14   428.2  909.99     434  913.47
#Mann= 3 ,-1,0
       0      .1       0  222.92    .045       0  265.42      .1       0
Bank Sta=222.92,265.42
XS Rating Curve= 0 ,0
Exp/Cntr(USF)=0,0
Exp/Cntr=0.3,0.1

Type RM Length L Ch R = 1 ,6600    ,290.6,291.4,282.5
XS GIS Cut Line= 6
1665029.13437651528262.5881293421665130.88384493528290.050016671
  1665189.502166528337.648018584 1665268.0512215528399.535362005
 1665325.8778775528447.328245416  1665392.529319528504.118486166
#Sta/Elev= 30
       0  872.05      13  863.33    26.6  856.18      30  853.34    36.8  845.72
    43.6   840.1    50.4  836.18    57.2  834.13    74.2   832.5   142.7  832.94
     168  830.25   184.5  831.05  190.57830.2909   197.4  829.27   210.4  829.84
   226.6  828.66   243.1  829.01  246.08830.2959   254.8  835.78   276.8  842.85
   294.5  853.83   306.1  863.52   327.1  878.91     332  882.09   344.8  887.57
     362  900.13   383.4  905.94   403.9  919.43   424.9  928.17   443.5  939.38
#Mann= 3 ,-1,0
       0      .1       0  190.57    .045       0  246.08      .1       0
Bank Sta=190.57,246.08
XS Rating Curve= 0 ,0
Exp/Cntr(USF)=0,0
Exp/Cntr=0.3,0.1

Type RM Length L Ch R = 1 ,6309    ,278.9,308.6,308.4
XS GIS Cut Line= 6
1664909.60771267528512.9212900851664990.47172417528547.870367169
1665055.60873301528585.3233762531665149.63971293528630.944348007
1665224.83149168528654.1929891711665310.53834125528680.399957761
#Sta/Elev= 30
       0  865.57    36.7  845.58      51  835.36    56.2  833.84    79.6   831.2
   118.4  830.58   139.6  832.42   154.8  830.36   170.5  831.33   173.3  831.04
  179.36828.5967   187.9  826.93   199.9  827.66   209.8     827   231.6  827.38
  244.87828.5944   268.1  832.17   278.4  836.94   305.9  859.38   319.6  873.23
     323  877.36   334.3  887.41   355.3  899.35   371.1  906.31     379  912.68
   388.2  922.01   398.5   927.2   419.1  934.41   429.4  940.64   436.1  946.87
#Mann= 3 ,-1,0
       0      .1       0  179.36    .045       0  244.87      .1       0
Bank Sta=179.36,244.87
XS Rating Curve= 0 ,0
Exp/Cntr(USF)=0,0
Exp/Cntr=0.3,0.1

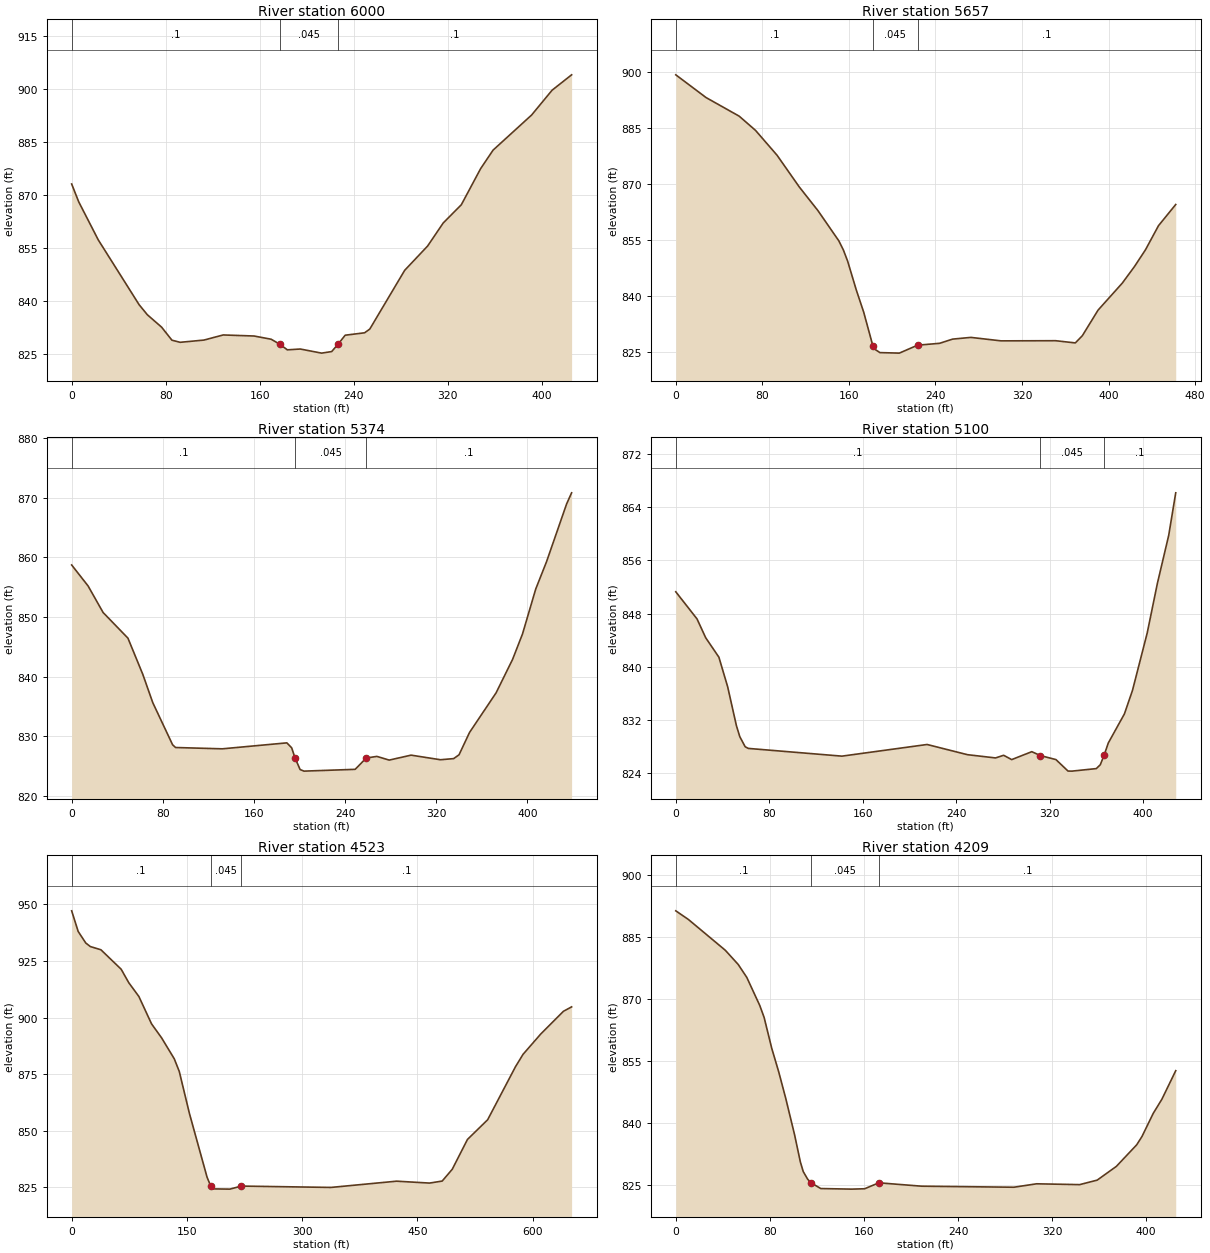
Type RM Length L Ch R = 1 ,6000    ,336.5,342.7,340.9
XS GIS Cut Line= 6
 1664807.6115256528679.8582921771664866.16816701528745.315838426
1664911.16873318528805.3153903341664971.16894126 528885.31523034
1665016.16917934528945.3151103411665068.66940242529015.314970344
#Sta/Elev= 30
       0  873.12       6  868.08    22.6  857.33    57.4  838.97    64.4  836.13
    76.5  832.63    85.3  828.94    92.3  828.34   112.5  828.97   128.9  830.42
   155.2  830.12   169.7  829.21  176.86827.8351   183.5  826.21   194.5  826.44
   212.6  825.28   221.2  825.72   226.7827.8357   232.7  830.35   249.2  831.03
   253.6  832.08   283.3   848.7   302.8  855.57   316.1   862.1   331.5  867.26
   347.9  877.46   358.5   882.7   391.3  892.64   408.7  899.65   425.3     904
#Mann= 3 ,-1,0
       0      .1       0  176.86    .045       0   226.7      .1       0
Bank Sta=176.86,226.7
XS Rating Curve= 0 ,0
Exp/Cntr(USF)=0,0
Exp/Cntr=0.3,0.1

Type RM Length L Ch R = 1 ,5657    ,282.2,283,282.2
XS GIS Cut Line= 2
1664524.29038297528814.9015640911664795.06287437529189.351143693
#Sta/Elev= 30
       0  899.24      28  893.14    58.6  888.15    73.7  884.34    93.6  877.67
   114.2  869.14   131.4  862.81   150.7  854.71   154.9  852.26   158.8   849.3
   166.9  841.47   173.7  835.56   182.1826.6133     183  825.81   188.7  824.72
   206.6  824.58   223.5  826.71   243.8  827.21   255.9  828.34   272.7   828.8
   300.7  827.87   351.1  827.91   369.3  827.32   375.8  829.26   390.3  836.11
   412.7  843.36   423.9  847.78   434.1  852.28   446.2  858.78   462.1  864.45
#Mann= 3 ,-1,0
       0      .1       0   182.1    .045       0   223.5      .1       0
Bank Sta=182.1,223.5
XS Rating Curve= 0 ,0
Exp/Cntr(USF)=0,0
Exp/Cntr=0.3,0.1

Type RM Length L Ch R = 1 ,5374    ,261.9,274.5,283.2
XS GIS Cut Line= 3
1664317.00847869 529017.898953221664498.50401137529225.659639004
1664607.09775738529347.106267217
#Sta/Elev= 30
       0  858.74    14.4  855.23    27.6  850.77    49.4  846.47    62.5  840.37
    71.2  835.65    88.6  828.59    91.2  828.13   132.2  827.91   188.9  828.91
   193.1  828.08  196.02826.3945   200.5  824.44   203.9  824.17   248.8  824.47
   258.6  826.37   267.9  826.64   278.7  826.02   297.9  826.85   323.7  826.08
   335.3  826.27     340  826.91   349.2  830.65   372.5  837.29     387  842.91
   395.7  847.17   407.3   854.7   416.8  859.29   434.4  868.97   438.8  870.84
#Mann= 3 ,-1,0
       0      .1       0  196.02    .045       0   258.6      .1       0
Bank Sta=196.02,258.6
XS Rating Curve= 0 ,0
Exp/Cntr(USF)=0,0
Exp/Cntr=0.3,0.1

Type RM Length L Ch R = 1 ,5100    ,599.9,576.5,547.5
XS GIS Cut Line= 6
1664172.76282154529075.2830673391664216.37362671529154.354431504
1664243.67737786529224.354947665 1664274.3302037529319.540780925
1664297.31998712529390.9304019151664324.14178386   529474.217965
#Sta/Elev= 30
       0  851.27    18.2  847.19    25.6  844.37    36.9  841.45    44.4  837.01
    51.9  831.16    54.8  829.51    59.4     828    62.1  827.75   142.2  826.59
   215.1  828.34   249.6  826.81   273.7  826.32   280.6  826.72   287.5  826.07
   304.7  827.26  312.03826.6805   325.4  826.07   335.7  824.35   339.1  824.34
   359.9  824.72   363.3  825.29  366.52826.6884   370.2  828.57     384  832.94
   390.9  836.47   403.5  845.09   412.2  852.53   421.9  859.75   427.9  866.13
#Mann= 3 ,-1,0
       0      .1       0  312.03    .045       0  366.52      .1       0
Bank Sta=312.03,366.52
XS Rating Curve= 0 ,0
Exp/Cntr(USF)=0,0
Exp/Cntr=0.3,0.1

Type RM Length L Ch R = 1 ,4523    ,323.2,314.1,304.7
XS GIS Cut Line= 2
1663592.93594627 529594.329502021664241.85645258529544.064406761
#Sta/Elev= 30
       0  947.16     8.5  938.04    18.4  932.94    24.3  931.38    38.1  929.96
    64.5  921.35    74.3  915.44    87.5  909.34     104  897.24   117.1  891.05
   133.6   881.8   140.1  876.23   153.3   857.7   176.3   829.5181.0867825.5592
   186.2  824.34     206  824.25220.8887825.5938   337.6     825   423.1  827.76
   465.9  826.92   482.4  827.81   495.5  833.02   515.3  846.19   541.6  854.89
   577.8  878.29   587.7  883.79   610.7  892.75   640.3   902.8   650.9  904.74
#Mann= 3 ,-1,0
       0      .1       0181.0867    .045       0220.8887      .1       0
Bank Sta=181.0867,220.8887
XS Rating Curve= 0 ,0
Exp/Cntr(USF)=0,0
Exp/Cntr=0.3,0.1

Type RM Length L Ch R = 1 ,4209    ,322.5,323.4,323.9
XS GIS Cut Line= 6
1663783.57103796529933.9330036391663861.94194421529894.905194555
1663927.90834771529859.2172738061664015.86191196529811.634363716
1664081.82601888529775.9474272181664158.78518255529734.312667971
#Sta/Elev= 30
       0  891.35    10.7  889.26    42.1  881.79    53.1  878.34    60.4   875.2
    71.4  868.41    75.1  865.52    81.6  858.01    87.6  852.24    93.5  845.88
     101  837.08   105.9  830.49   108.4  828.12   112.2  826.26     115  825.41
   123.3  824.02   149.5  823.88   160.6  823.97  172.62825.4102   209.1  824.59
   287.5  824.34   306.8  825.17   343.4  824.97   358.3  826.06   374.6  829.39
   391.9  834.62   396.4  836.64     406  842.26   413.3  845.66   425.1  852.59
#Mann= 3 ,-1,0
       0      .1       0     115    .045       0  172.62      .1       0
Bank Sta=115,172.62
XS Rating Curve= 0 ,0
Exp/Cntr(USF)=0,0
Exp/Cntr=0.3,0.1

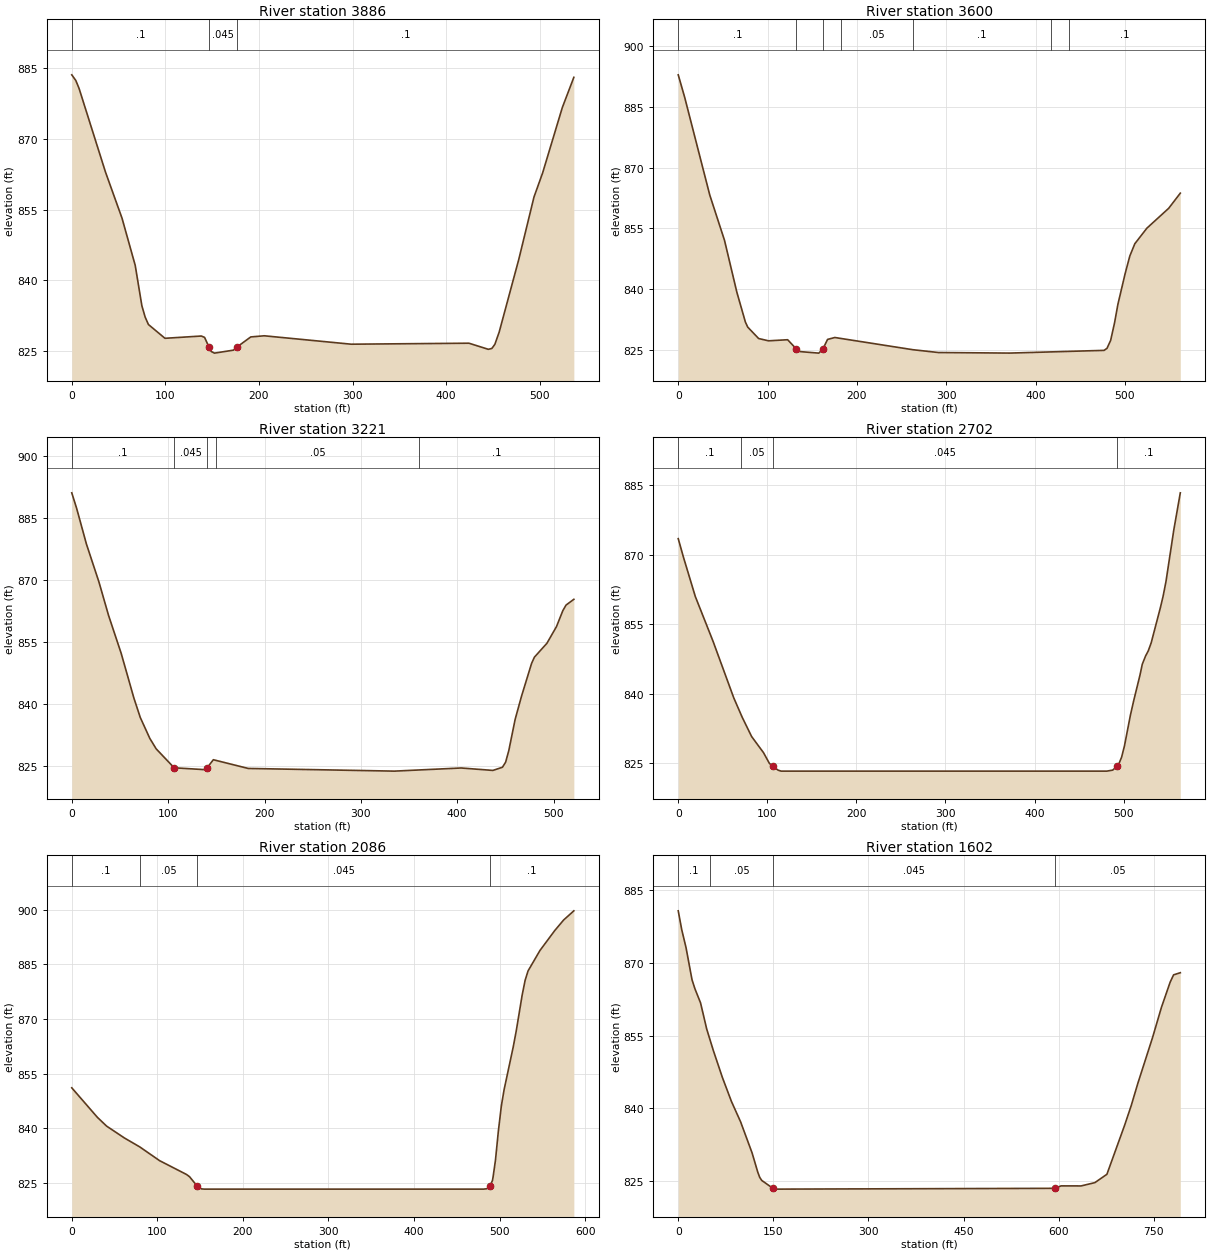
Type RM Length L Ch R = 1 ,3886    ,293.2,286.3,276.2
XS GIS Cut Line= 3
1663915.69348694530203.8976428681664186.48687192530096.640046925
1664371.80669419529936.086464127
#Sta/Elev= 30
       0  883.53     4.3  882.34     7.8  880.65      36  862.96    53.7  853.18
    67.8  843.19    74.9  834.65    78.4  832.25    81.9  830.67    99.6  827.75
   138.4  828.23   141.9  827.95  146.47825.9612     149  824.96   152.5  824.61
   172.8  825.24     177825.9731   191.3  828.04   205.7  828.28   298.6   826.5
   424.4  826.71   445.1  825.42   448.9   825.6   452.1  826.47   456.7  829.05
   477.7  844.48   493.9  857.65   503.2   862.8   524.2  876.61   536.5     883
#Mann= 3 ,-1,0
       0      .1       0  146.47    .045       0     177      .1       0
Bank Sta=146.47,177
XS Rating Curve= 0 ,0
Exp/Cntr(USF)=0,0
Exp/Cntr=0.3,0.1

Type RM Length L Ch R = 1 ,3600    ,388.7,378.3,373.7
XS GIS Cut Line= 6
1664179.19019319530463.0491742011664230.80393511530392.393147539
1664275.04433219530331.8309327031664334.03174703 530251.08142228
1664378.27214411530190.5188793651664510.67616711 530009.15057338
#Sta/Elev= 30
       0  892.96     7.2  887.42    35.3  863.26    51.8  852.07    65.6  839.27
    75.2  831.86    77.8  830.62      90   827.8   101.1  827.23   122.5   827.5
  132.24825.2236   136.3  824.57   157.4  824.19  161.93 825.202   167.2  827.58
   175.3  828.05   262.5  825.04   291.2  824.34   371.1   824.2   476.7  824.87
     480  825.37   484.1  827.33   488.5   831.7   492.2  836.22   500.3  843.81
   505.6  848.21   511.2  851.23   524.7  855.07   549.1  859.98   562.1  863.72
#Mann= 7 ,-1,0
       0      .1       0  132.24    .045       0  161.93      .1       0
   182.5     .05       0   262.5      .1       0   417.5     .05       0
   437.5      .1       0
Bank Sta=132.24,161.93
XS Rating Curve= 0 ,0
Exp/Cntr(USF)=0,0
Exp/Cntr=0.3,0.1

Type RM Length L Ch R = 1 ,3221    ,487.9,519.8,613
XS GIS Cut Line= 2
1664603.67087321530543.125699316 1664655.0734068530024.627367121
#Sta/Elev= 30
       0  891.12     5.1  887.33    15.2  878.73    28.2  869.54    38.1  861.51
    51.3  852.25    64.5  841.42    71.1  836.74      81  831.68    87.6  829.15
  106.25824.5677     137  824.13   140.7824.6376   146.9  826.52   183.1  824.41
   334.8  823.76   404.1  824.52     437  823.93   446.9   824.7   450.2  825.92
   453.5  828.73   460.1   836.3   466.7  841.89   477.1   849.8   480.1  851.35
   493.1  854.72     503  858.75   509.6  862.61   512.9  863.95     521  865.35
#Mann= 5 ,-1,0
       0      .1       0  106.25    .045       0   140.7      .1       0
     150     .05       0     360      .1       0
Bank Sta=106.25,140.7
XS Rating Curve= 0 ,0
Exp/Cntr(USF)=0,0
Exp/Cntr=0.3,0.1

Type RM Length L Ch R = 1 ,2702    ,603.8,615.3,660.4
XS GIS Cut Line= 2
1665043.85295498 530586.535041661665133.58272658530030.002652112
#Sta/Elev= 30
       0  873.44     5.9  869.41    19.2  860.95    39.2  851.25    62.4  839.08
    71.9  834.89    82.4  830.77    95.7   827.3   102.3     825  105.96824.3398
   112.3   823.5   115.6  823.31   481.2  823.31   487.8  823.53  492.58824.3395
   494.5  824.78   497.8  826.32     501  828.76   507.7  835.39   511.1  838.28
   518.4     844     521  846.36   524.7  848.14   527.7  849.23     531  850.97
   541.3  858.54   544.3  860.95   547.6  864.18   556.4  875.33   563.7  883.32
#Mann= 4 ,-1,0
       0      .1       0      70     .05       0  105.96    .045       0
  492.58      .1       0
Bank Sta=105.96,492.58
XS Rating Curve= 0 ,0
Exp/Cntr(USF)=0,0
Exp/Cntr=0.3,0.1

Type RM Length L Ch R = 1 ,2086    ,447.4,484.1,641.8
XS GIS Cut Line= 2
 1665612.0818613530681.188671752 1665803.5159236530126.592932429
#Sta/Elev= 30
       0   851.1      30  842.99    40.7   840.6    61.8   837.3    79.4   834.9
   102.7  831.11   134.1  827.33   137.6  826.72  146.43824.1865   151.5  823.38
   154.9  823.31   481.2  823.31   484.7   823.4   488.1  823.83  488.82824.1855
   491.6  825.68   492.3  826.61   495.1  831.24   498.5  839.23     502  846.15
   505.2  850.59   515.9  862.35   519.4  866.73   526.3  876.53   529.8  880.62
   533.2  883.17   547.1  888.77   564.4  894.24   574.8  897.14   586.7  899.65
#Mann= 4 ,-1,0
       0      .1       0      80     .05       0  146.43    .045       0
  488.82      .1       0
Bank Sta=146.43,488.82
XS Rating Curve= 0 ,0
Exp/Cntr(USF)=0,0
Exp/Cntr=0.3,0.1

Type RM Length L Ch R = 1 ,1602    ,459.7,457.4,588.8
XS GIS Cut Line= 2
1665928.17368984530877.7967722011666503.81704127530333.872637289
#Sta/Elev= 30
       0  880.73     5.5  876.85    12.3  873.14    21.7  866.54    26.2   864.7
    35.2  861.74    44.9  856.35    55.3  851.94    69.6  846.37    83.9  841.41
    98.4  837.19   116.5  830.78   125.5   826.8   128.5  825.75   131.7  825.11
  149.33823.4748   155.6  823.31  594.11823.4749   603.9  823.98   635.5  823.97
   657.2  824.65   676.2  826.37   704.1  836.47   714.5  840.52   724.9  845.09
   748.2  854.58   762.2   860.8     776  866.02   781.4  867.52     792  867.96
#Mann= 4 ,-1,0
       0      .1       0      50     .05       0  149.33    .045       0
  594.11     .05       0
Bank Sta=149.33,594.11
XS Rating Curve= 0 ,0
Exp/Cntr(USF)=0,0
Exp/Cntr=0.3,0.1

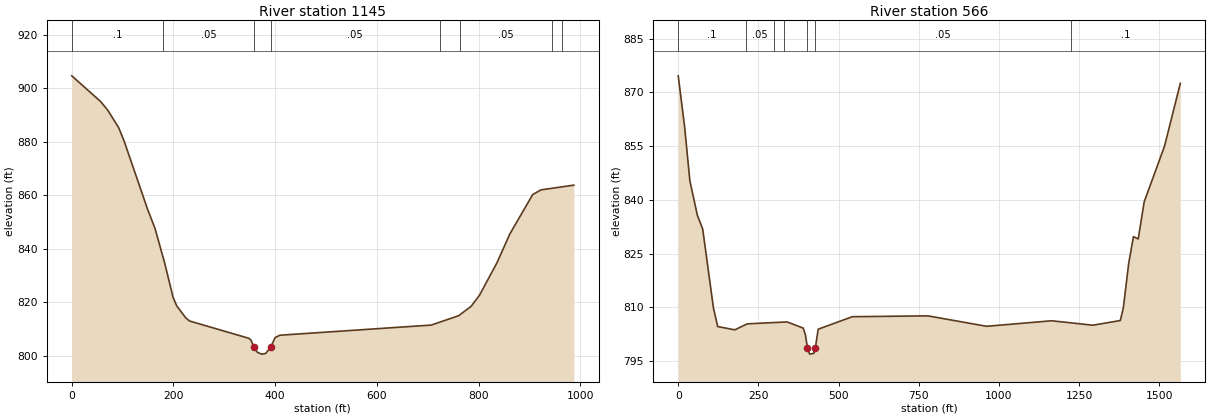
Type RM Length L Ch R = 1 ,1145    ,561.8,578.3,588.3
XS GIS Cut Line= 3
1666068.88201783531210.6749810621666366.70085887531084.195143595
1666897.78680622530685.880683083
#Sta/Elev= 30
       0  904.67    56.7  895.08      71  891.77    92.4  885.24   103.1  880.21
   149.4  854.64   163.6  847.69   182.5  834.86   199.3  821.81   206.4  818.68
   224.2  814.17   231.4  813.03   348.7  806.52   352.8  805.74  358.42803.1568
   365.1  801.31   373.3  800.63   381.2  800.86  390.96 803.154     400  806.83
   409.4   807.7     707  811.49   760.9     815   785.5  818.52   801.9  822.67
   835.9  834.66   861.6  845.57   906.5  860.28   922.9  862.04   987.4   863.8
#Mann= 8 ,-1,0
       0      .1       0     180     .05       0  358.42    .045       0
  390.96     .05       0  723.56      .1       0  763.56     .05       0
  943.56      .1       0  963.56     .05       0
Bank Sta=358.42,390.96
XS Rating Curve= 0 ,0
Exp/Cntr(USF)=0,0
Exp/Cntr=0.3,0.1

Type RM Length L Ch R = 1 ,566     ,,,
XS GIS Cut Line= 4
1666003.29742668531524.9605703341666546.38904933531621.918377816
1666764.72745216531574.6368058561667138.44094133530878.439640126
#Sta/Elev= 30
       0  874.61    19.7  860.55    36.3  845.29    59.7  835.67    76.3  831.83
   109.7  809.85     123  804.62   176.3   803.7   215.1  805.37   339.6  805.91
   389.6  804.18   396.3  802.38  402.97798.5941   409.6  796.92   422.9  797.14
  427.36798.5934   436.3  803.88   542.9  807.37   778.7   807.6   961.1  804.69
  1164.6  806.23  1292.5  804.99  1378.2   806.3  1387.6  809.88  1404.2  822.19
  1419.1  829.72    1434  829.07  1452.6  839.43    1516  854.98  1565.2  872.51
#Mann= 7 ,-1,0
       0      .1       0     210     .05       0     300      .1       0
     330     .05       0  402.97    .045       0  427.36     .05       0
 1225.08      .1       0
Bank Sta=402.97,427.36
XS Rating Curve= 0 ,0
Exp/Cntr(USF)=0,0
Exp/Cntr=0.3,0.1
LCMann Table=0

Chan Stop Cuts=-1
Use User Specified Reach Order=0
Composite Channel Slope=5